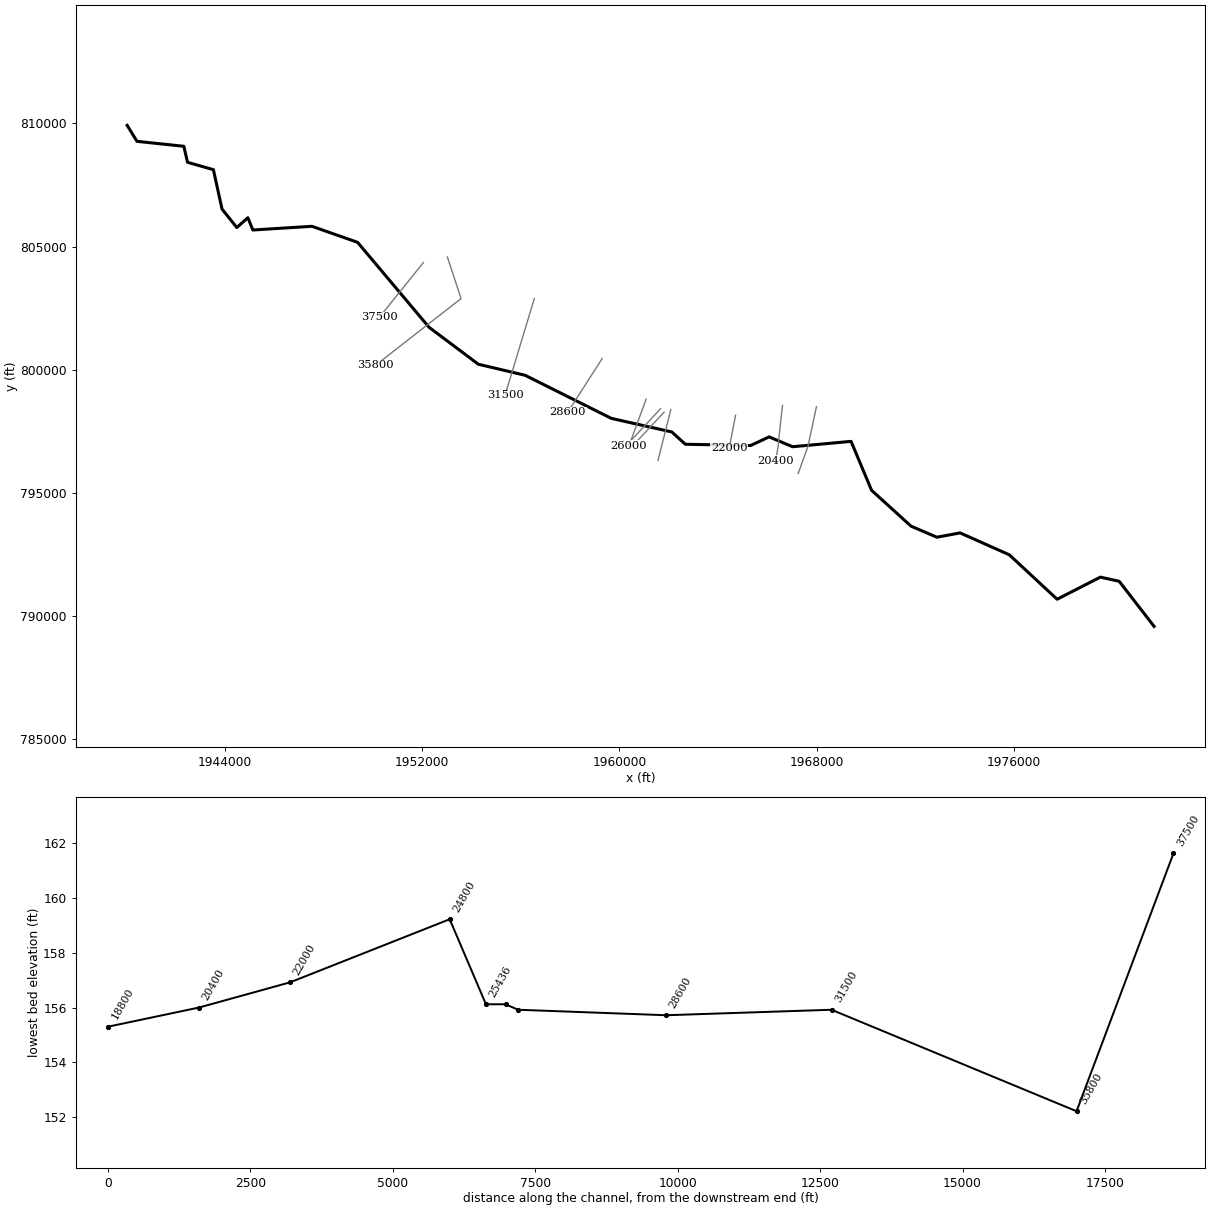
--- CCR_SALUDA_RIVER.prj (project) ---

Proj Title=CCR SALUDA RIVER Detailed Study
Current Flow=f10
Current HD=h01
Default Exp/Contr=0.3,0.1
English Units
Geom File=g02
Geom File=g13
Geom File=g12
Geom File=g27
Geom File=g01
Flow File=f01
Flow File=f02
Flow File=f03
Flow File=f04
Flow File=f05
Flow File=f06
Flow File=f07
Flow File=f08
Flow File=f09
Flow File=f10
Plan File=p19
Plan File=p20
Plan File=p21
Plan File=p24
Plan File=p03
Plan File=p04
Plan File=p15
Plan File=p01
HD File=h01
Background Map Layer=Ineffectives
Y Axis Title=Elevation
X Axis Title(PF)=Main Channel Distance
X Axis Title(XS)=Station
BEGIN DESCRIPTION:
SALUDA RIVER
END DESCRIPTION:
DSS File=..\CCR1SaludaRiver.dss
DSS Export Rating Curves= 0
DSS Export Rating Curve Sorted= 0
DSS Export Volume Flow Curves= 0
DXF Filename=..\..\..\..\..\..\APPLICATIONS\HECRAS\Saluda River\Preliminary Model 2-2018\SALUDA RIVER\SALUDA RIVER\Simulations\SaludaRiver\SALUDA RIVER.
DXF OffsetX= 0
DXF OffsetY= 0
DXF ScaleX= 1
DXF ScaleY= 10

--- CCR_SALUDA_RIVER.p01 (plan) ---

Plan Title=SCOUR
Program Version=6.10
Short Identifier=SCOUR
Geom File=g01
Flow File=f10
Subcritical Flow
K Sum by GR= 0
Std Step Tol= 0.01
Critical Tol= 0.01
Num of Std Step Trials= 20
Max Error Tol= 0.3
Flow Tol Ratio= 0.001
Split Flow NTrial= 30
Split Flow Tol= 0.02
Split Flow Ratio= 0.02
Log Output Level= 0
Friction Slope Method= 1
Unsteady Friction Slope Method= 2
Unsteady Bridges Friction Slope Method= 1
Parabolic Critical Depth
Global Vel Dist= 1 , 1 , 1
Global Log Level= 0
CheckData=True
Encroach Param=-1 ,0,0, 0
Computation Interval=1MIN
Output Interval=1HOUR
Instantaneous Interval=1HOUR
Mapping Interval=1HOUR
Computation Time Step Use Courant=        0
Computation Time Step Use Time Series=    0
Computation Time Step Count To Double=0
Computation Time Step Max Doubling=0
Computation Time Step Max Halving=0
Computation Time Step Residence Courant=0
Run HTab= 0
Run UNet= 0
Run Sediment= 0
Run PostProcess= 0
Run WQNet= 0
Run RASMapper= 0
UNET Theta= 1
UNET Theta Warmup= 1
UNET ZTol= 0.02
UNET ZSATol= 0.02
UNET MxIter= 20
UNET Max Iter WO Improvement= 0
UNET MaxInSteps= 0
UNET DtIC= 0
UNET DtMin= 0
UNET MaxCRTS= 20
UNET WFStab= 2
UNET SFStab= 1
UNET WFX= 1
UNET SFX= 1
UNET Gravity=32.174
UNET 1D Methodology=Finite Difference
UNET DSS MLevel= 4
UNET Pardiso=0
UNET DZMax Abort= 100
UNET Use Existing IB Tables=-1
UNET Froude Reduction=False
UNET Froude Limit= 0.8
UNET Froude Power= 4
UNET D1 Cores= 0
UNET WindReference=Eulerian
UNET WindDragFormulation=Hsu (1988)
UNET D2 Coriolis=0
UNET D2 Cores= 0
UNET D2 Theta= 1
UNET D2 Theta Warmup= 1
UNET D2 Z Tol= 0.01
UNET D2 Volume Tol= 0.01
UNET D2 Max Iterations= 20
UNET D2 Equation= 0
UNET D2 RampUpFraction=0.1
UNET D2 TimeSlices= 1
UNET D2 Turbulence Formulation=Non-Conservative (original)
UNET D2 Smagorinsky Mixing=0
UNET D2 BCVolumeCheck=0
UNET D2 Cores=0
UNET D2 SolverType=PARDISO (Direct)
UNET D2 Minimum Iterations= 2147483647
UNET D2 Maximum Iterations= 2147483647
UNET D2 Restart Number= 10
UNET D2 Relaxation Coeff=1.3
UNET D2 SOR Precondition Iterations= 10
UNET D2 ILUT Maximum Fill= 8
UNET D2 ILUT Tolerance=1E-08
UNET D1D2 MaxIter= 0
UNET D1D2 ZTol=0.01
UNET D1D2 QTol=0.1
UNET D1D2 MinQTol=1
Write IC File= 0
Write IC File at Fixed DateTime=0
Write IC File at Sim End=0
Echo Input=False
Echo Parameters=False
Echo Output=False
Write Detailed= 0
HDF Write Warmup=0
HDF Write Time Slices=0
HDF Flush=0
HDF Compression= 1
HDF Chunk Size= 1
HDF Spatial Parts= 1
HDF Use Max Rows=0
HDF Fixed Rows= 1
Calibration Method= 0
Calibration Iterations= 20
Calibration Max Change=0.05
Calibration Tolerance=0.2
Calibration Maximum=1.5
Calibration Minimum=0.5
Calibration Optimization Method= 1
WQ AD Non Conservative
WQ ULTIMATE=-1
WQ Max Comp Step=1HOUR
WQ Output Interval=15MIN
WQ Output Selected Increments= 0
WQ Output face flow=0
WQ Output face velocity=0
WQ Output face area=0
WQ Output face dispersion=0
WQ Output cell volume=0
WQ Output cell surface area=0
WQ Output cell continuity=0
WQ Output cumulative cell continuity=0
WQ Output face conc=0
WQ Output face dconc_dx=0
WQ Output face courant=0
WQ Output face peclet=0
WQ Output face adv mass=0
WQ Output face disp mass=0
WQ Output cell mass=0
WQ Output cell source sink temp=0
WQ Output nsm pathways=0
WQ Output nsm derived pathways=0
WQ Create Restart=0
WQ Fixed Restart=0
WQ System Summary=0
WQ Write To DSS=0
Sorting and Armoring Iterations= 10
XS Update Threshold= 0.02
Bed Roughness Predictor= 0
Hydraulics Update Threshold= 0.02
Energy Slope Method= 1
Volume Change Method= 1
Sediment Retention Method= 0
Sediment TS Multiplier= 1
Warm Up Method= 0
XS Weighting Method= 0
Number of US Weighted Cross Sections= 1
Number of DS Weighted Cross Sections= 1
Upstream XS Weight=0
Main XS Weight=1
Downstream XS Weight=0
Number of DS XS's Weighted with US Boundary= 1
Upstream Boundary Weight= 1
Weight of XSs Associated with US Boundary= 0
Number of US XS's Weighted with DS Boundary= 1
Downstream Boundary Weight= 0.5
Weight of XSs Associated with DS Boundary= 0.5
Percentile Method= 0
Sediment Output Level= 4
Mass or Volume Output= 0
Output Increment Type= 1
Profile and TS Output Increment= 1
Transport Output Increment 1
XS Output Flag= 0
XS Output Increment= 10
Read HDF5 Sediment Hotstart= 0
Sediment Hotstart Type= 0
Write Gradation File= 0
Read Gradation Hotstart= 0
Write HDF5 File= 1
Write Binary Output= 1
Write DSS Sediment File= 0
DSS Sediment Output Type= 1
SV Curve= 0
Specific Gage Flag= 0
Subcell Erosion Methods= 0
Subcell Deposition Methods= 0
Advection Scheme= 1
Matrix Solver= 0
Implicit Weighting Factor= 1
Maximum Outer Loop Convergence Iterations= 5
Convergence Maximum Absolute= 0.001
Convergence RMSE= 0.0001
Grain Fractions Max Abs Error= 0.001
Max Subgrid Regions= 1
Max Subgrid Length Scale= 3.402823E+38
Initial Layer Thickness= 3.402823E+38
Min Layer Thickness= 3.402823E+38
Max Layer Thickness= 3.402823E+38
Number of Layers= 5

--- CCR_SALUDA_RIVER.p03 (plan) ---

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Plan Title=FW_CEM
Short Identifier=FW_CEM
Geom File=g12
Flow File=f02
Encroach Param=-1 ,0,0, 2
Encroach River=SALUDA RIVER
Encroach Reach=Reach-1
Encroach Node=37500
       1     980    1940
Encroach Node=35800
       1    3820    6820
Encroach Node=31500
       1    3000    5010
Encroach Node=28600
       1     700    2400
Encroach Node=26000
       1  578.67 1913.63
Encroach Node=25780
       1  578.67 1913.63
Encroach Node=25436
       1  661.99    1692
Encroach Node=24800
       1  661.99    1692
Encroach Node=22000
       1  981.14 1920.25
Encroach Node=18800
       1    3965    5393
Encroach Node=18200
       1    4500    5425
Encroach Node=17840
       1    4840    5240
Encroach Node=17750
       1    4840    5240
Encroach Node=17665
       1    4660    5290
Encroach Node=17385
       1    4730    5330
Encroach Node=17365
       1    4700    5300
Encroach Node=17000
       1    4700    5300
Encroach Node=16600
       1    4700    5300
Encroach Node=16200
       1    4640    5350
Encroach Node=15700
       1    4700    5500
Encroach Node=15200
       1    4640    5560
Encroach Node=14700
       1    4735    5598
Encroach Node=14200
       1    4800    5540
Encroach Node=13600
       1    4800    5500
Encroach Node=13000
       1    4821    5340
Encroach Node=12500
       1    4821    5382
Encroach Node=12000
       1    4842    5120
Encroach Node=11500
       1    4839    5215
Encroach Node=11000
       1    4834    5179
Encroach Node=10500
       1    4801    5195
Encroach Node=10000
       1    4820    5205
Encroach Node=9500
       1    4810    5220
Encroach Node=9000
       1    4817    5200
Encroach Node=8500
       1    4728    5285
Encroach Node=8240
       1    4640    5465
Encroach Node=7900
       1    4720    5565
Encroach Node=7400
       1    4728    5253
Encroach Node=6900
       1    4762    5167
Encroach Node=6450
       1    4730    5193
Encroach Node=6270
       1    4719    5204
Encroach Node=5900
       1    4830    5165
Encroach Node=5400
       1    4795    5150
Encroach Node=4900
       1    4830    5150
Encroach Node=4400
       1    4880    5150
Encroach Node=3900
       1    4860    5150
Encroach Node=3400
       1    4844    5150
Encroach Node=2900
       1    4700    5275
Encroach Node=2400
       1    4550    5675
Encroach Node=2000
       1    4750    5700
Encroach Node=1600
       1    4750    5600
Encroach Node=1100
       1    4750    5350
BEGIN DESCRIPTION:
Floodway Run
END DESCRIPTION:
UNET D2 Eddy Viscosity=0.3
UNET D2 Transverse Eddy Viscosity=0.3
Sediment Output Level= 3

--- CCR_SALUDA_RIVER.p04 (plan) ---

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Plan Title=FW_REV
Short Identifier=FW_REV
Geom File=g13
Flow File=f02
Encroach Param=-1 ,0,0, 2
Encroach River=SALUDA RIVER
Encroach Reach=Reach-1
Encroach Node=37500
       1     980    1940
Encroach Node=35800
       1    3820    6820
Encroach Node=31500
       1    3000    5010
Encroach Node=28600
       1     700    2400
Encroach Node=26000
       1  578.67 1913.63
Encroach Node=25780
       1  578.67 1913.63
Encroach Node=25436
       1  661.99    1692
Encroach Node=24800
       1  661.99    1692
Encroach Node=22000
       1  981.14 1920.25
Encroach Node=18800
       1    3965    5393
Encroach Node=18200
       1    4500    5425
Encroach Node=17840
       1    4840    5240
Encroach Node=17750
       1    4840    5240
Encroach Node=17665
       1    4660    5290
Encroach Node=17365
       1    4700    5300
Encroach Node=17000
       1    4700    5300
Encroach Node=16600
       1    4700    5300
Encroach Node=16200
       1    4640    5350
Encroach Node=15700
       1    4700    5500
Encroach Node=15200
       1    4640    5560
Encroach Node=14700
       1    4735    5598
Encroach Node=14200
       1    4800    5540
Encroach Node=13600
       1    4800    5500
Encroach Node=13000
       1    4821    5340
Encroach Node=12500
       1    4821    5382
Encroach Node=12000
       1    4842    5120
Encroach Node=11500
       1    4839    5215
Encroach Node=11000
       1    4834    5179
Encroach Node=10500
       1    4801    5195
Encroach Node=10000
       1    4820    5205
Encroach Node=9500
       1    4810    5220
Encroach Node=9000
       1    4817    5200
Encroach Node=8500
       1    4728    5285
Encroach Node=8240
       1    4640    5465
Encroach Node=7900
       1    4720    5565
Encroach Node=7400
       1    4728    5253
Encroach Node=6900
       1    4762    5167
Encroach Node=6450
       1    4730    5193
Encroach Node=6270
       1    4719    5204
Encroach Node=5900
       1    4830    5165
Encroach Node=5400
       1    4795    5150
Encroach Node=4900
       1    4830    5150
Encroach Node=4400
       1    4880    5150
Encroach Node=3900
       1    4860    5150
Encroach Node=3400
       1    4844    5150
Encroach Node=2900
       1    4700    5275
Encroach Node=2400
       1    4550    5675
Encroach Node=2000
       1    4750    5700
Encroach Node=1600
       1    4750    5600
Encroach Node=1100
       1    4750    5350
BEGIN DESCRIPTION:
Floodway Run
END DESCRIPTION:
UNET D2 Eddy Viscosity=0.3
UNET D2 Transverse Eddy Viscosity=0.3
Sediment Output Level= 3

--- CCR_SALUDA_RIVER.p15 (plan) ---

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Plan Title=Natural_Conditions
Short Identifier=NATURAL
Geom File=g27
Flow File=f10

--- CCR_SALUDA_RIVER.p19 (plan) ---

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Plan Title=Sensitivity Analysis
Program Version=6.00
Short Identifier=Sensitivity_Analysis
Geom File=g12
Flow File=f08
BEGIN DESCRIPTION:
This is the Richland County Prelminary model combined with the HEC-2 Effective model for Lexington County with updated I-26 and I-20 Bridges from mapping.
END DESCRIPTION:

--- CCR_SALUDA_RIVER.p20 (plan) ---

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Plan Title=CEM
Short Identifier=CEM
Geom File=g12
Flow File=f10
BEGIN DESCRIPTION:
"	Corrected Effective Model: The Corrected Effective model was created by duplicating and modifying the DEM. The changes from the DEM to the CEM are highlighted below.
o	XS 17472 added as the location of the downstream boundary cross section for the existing bridge as well as the bounding upstream cross section for the proposed bridge in the Revised Model.
o	XS 17471 added as the location of the upstream bounding cross section for the proposed bridge to allow input into the Revised Model.
o	Pier widths were updated to 4.0' based upon asbuilt drawings
o	Revised manning's n value of XS 17000 to 0.045 for the channel
o	Updated existing I-26 bridge distance to upstream XS to 30'
o	Updated length of I-26 bridge to 536' in length and 160' in width. The existing bridge is skewed compared the centerline of the Saluda River resulting in a shorter effective opening width as well as longer width across the skewed bridge section.
END DESCRIPTION:

--- CCR_SALUDA_RIVER.p21 (plan) ---

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Plan Title=REV
Short Identifier=REV
Geom File=g13
Flow File=f10
Global Vel Dist= 30 , 5 , 10
Vel Dist Location=SALUDA RIVER    ,Reach-1         ,37500   , 37 , 3 , 4
Vel Dist Location=SALUDA RIVER    ,Reach-1         ,35800   , 37 , 3 , 4
Vel Dist Location=SALUDA RIVER    ,Reach-1         ,31500   , 37 , 3 , 4
Vel Dist Location=SALUDA RIVER    ,Reach-1         ,28600   , 37 , 3 , 4
Vel Dist Location=SALUDA RIVER    ,Reach-1         ,26000   , 37 , 3 , 4
Vel Dist Location=SALUDA RIVER    ,Reach-1         ,25780   , 37 , 3 , 4
Vel Dist Location=SALUDA RIVER    ,Reach-1         ,25550   , 37 , 3 , 4
Vel Dist Location=SALUDA RIVER    ,Reach-1         ,25436   , 37 , 3 , 4
Vel Dist Location=SALUDA RIVER    ,Reach-1         ,24800   , 37 , 3 , 4
Vel Dist Location=SALUDA RIVER    ,Reach-1         ,22000   , 37 , 3 , 4
Vel Dist Location=SALUDA RIVER    ,Reach-1         ,18800   , 37 , 3 , 4
Vel Dist Location=SALUDA RIVER    ,Reach-1         ,18200   , 37 , 3 , 4
Vel Dist Location=SALUDA RIVER    ,Reach-1         ,17840   , 37 , 3 , 4
Vel Dist Location=SALUDA RIVER    ,Reach-1         ,17790   , 37 , 3 , 4
Vel Dist Location=SALUDA RIVER    ,Reach-1         ,17750   , 37 , 3 , 4
Vel Dist Location=SALUDA RIVER    ,Reach-1         ,17665   , 37 , 3 , 4
Vel Dist Location=SALUDA RIVER    ,Reach-1         ,17540   , 37 , 3 , 4
Vel Dist Location=SALUDA RIVER    ,Reach-1         ,17365   , 37 , 3 , 4
Vel Dist Location=SALUDA RIVER    ,Reach-1         ,17000   , 37 , 3 , 4
Vel Dist Location=SALUDA RIVER    ,Reach-1         ,16600   , 37 , 3 , 4
Vel Dist Location=SALUDA RIVER    ,Reach-1         ,16200   , 37 , 3 , 4
Vel Dist Location=SALUDA RIVER    ,Reach-1         ,15700   , 37 , 3 , 4
Vel Dist Location=SALUDA RIVER    ,Reach-1         ,15200   , 37 , 3 , 4
Vel Dist Location=SALUDA RIVER    ,Reach-1         ,14700   , 37 , 3 , 4
Vel Dist Location=SALUDA RIVER    ,Reach-1         ,14200   , 37 , 3 , 4
Vel Dist Location=SALUDA RIVER    ,Reach-1         ,13600   , 37 , 3 , 4
Vel Dist Location=SALUDA RIVER    ,Reach-1         ,13000   , 37 , 3 , 4
Vel Dist Location=SALUDA RIVER    ,Reach-1         ,12500   , 37 , 3 , 4
Vel Dist Location=SALUDA RIVER    ,Reach-1         ,12000   , 37 , 3 , 4
Vel Dist Location=SALUDA RIVER    ,Reach-1         ,11500   , 37 , 3 , 4
Vel Dist Location=SALUDA RIVER    ,Reach-1         ,11000   , 37 , 3 , 4
Vel Dist Location=SALUDA RIVER    ,Reach-1         ,10500   , 37 , 3 , 4
Vel Dist Location=SALUDA RIVER    ,Reach-1         ,10000   , 37 , 3 , 4
Vel Dist Location=SALUDA RIVER    ,Reach-1         ,9500    , 37 , 3 , 4
Vel Dist Location=SALUDA RIVER    ,Reach-1         ,9000    , 37 , 3 , 4
Vel Dist Location=SALUDA RIVER    ,Reach-1         ,8500    , 37 , 3 , 4
Vel Dist Location=SALUDA RIVER    ,Reach-1         ,8240    , 37 , 3 , 4
Vel Dist Location=SALUDA RIVER    ,Reach-1         ,7900    , 37 , 3 , 4
Vel Dist Location=SALUDA RIVER    ,Reach-1         ,7400    , 37 , 3 , 4
Vel Dist Location=SALUDA RIVER    ,Reach-1         ,6900    , 37 , 3 , 4
Vel Dist Location=SALUDA RIVER    ,Reach-1         ,6450    , 37 , 3 , 4
Vel Dist Location=SALUDA RIVER    ,Reach-1         ,6350    , 37 , 3 , 4
Vel Dist Location=SALUDA RIVER    ,Reach-1         ,6270    , 37 , 3 , 4
Vel Dist Location=SALUDA RIVER    ,Reach-1         ,5900    , 37 , 3 , 4
Vel Dist Location=SALUDA RIVER    ,Reach-1         ,5400    , 37 , 3 , 4
Vel Dist Location=SALUDA RIVER    ,Reach-1         ,4900    , 37 , 3 , 4
Vel Dist Location=SALUDA RIVER    ,Reach-1         ,4400    , 37 , 3 , 4
Vel Dist Location=SALUDA RIVER    ,Reach-1         ,3900    , 37 , 3 , 4
Vel Dist Location=SALUDA RIVER    ,Reach-1         ,3400    , 37 , 3 , 4
Vel Dist Location=SALUDA RIVER    ,Reach-1         ,2900    , 37 , 3 , 4
Vel Dist Location=SALUDA RIVER    ,Reach-1         ,2400    , 37 , 3 , 4
Vel Dist Location=SALUDA RIVER    ,Reach-1         ,2000    , 37 , 3 , 4
Vel Dist Location=SALUDA RIVER    ,Reach-1         ,1600    , 37 , 3 , 4
Vel Dist Location=SALUDA RIVER    ,Reach-1         ,1100    , 37 , 3 , 4
BEGIN DESCRIPTION:
REV MODEL: CEM Duplicated
o	Proposed Bridge at XS 17540 was updated to reflect the profile of the proposed bridges for Phase 1 and 3. Width was entered in as 273 feet which combines the lengths of both the Proposed I-26 Bridge as well as the CD lane bridge to be constructed in Phase 1.
o	Ineffective flow areas for the downstream cross-section were updated to reflect the proposed bridge. Minimal changes were made to the effective flow width due to the existing terrain near the river crossing.
o	Piers were added to proposed bridge at a width of 6.5 feet for the proposed drilled shafts. Drag coefficient (Cd) added to reflect circular columns.
o	XS 17385 was removed to allow the full width of the proposed bridge to be modeled.
o	XS 16600 and XS 16200 were modified to show the realigned access road to be constructed. The realigned access road is located within the Saluda River floodplain. Ground elevations were updated within the HEC-RAS model based upon the roadway profiles and cross sections for proposed access road.
END DESCRIPTION:

--- CCR_SALUDA_RIVER.p24 (plan) ---

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Plan Title=DEM
Program Version=6.00
Short Identifier=DEM
Geom File=g02
Flow File=f03
BEGIN DESCRIPTION:
"	Duplicate Effective Model: The Effective model was created by HDR utilizing the effective model/output data provided by both Lexington and Richland County. The HEC-RAS model provided by Richland County was used as the starting point for duplicating and combining the effective models/outputs. The Richland County models upstream boundary is FEMA Cross Section N along the Saluda river and extends downstream to the confluence point of the Saluda River and the Congaree River. The model was than extended upstream into Lexington County based upon the HEC-2 data provided by Lexington County. Datum adjustment from NGVD29 to NAVD88 was done to ensure the two models were on the same and latest datum. Flows upstream of cross section N were updated from the SCDOT's model to reflect the Lexington County FIS report. The Lexington County FIS indicates a flow change at XS N that was utilized in the Richland County effective model and applied downstream to the confluence of the Saluda with the Congaree River.
END DESCRIPTION:

--- CCR_SALUDA_RIVER.f01 (steady flow) ---

Flow Title=Multiple
Program Version=5.03
Number of Profiles= 5
Profile Names=10-year,25-year,50-year,100-year,500-year
River Rch & RM=SALUDA RIVER,Reach-1         ,18580
   29600   39400   48300   58600   89900
River Rch & RM=SALUDA RIVER,Reach-1         ,17665
   29600   39400   48300   58600   89900
Boundary for River Rch & Prof#=SALUDA RIVER,Reach-1         , 1
Up Type= 0
Dn Type= 3
Dn Slope=0.00105
Boundary for River Rch & Prof#=SALUDA RIVER,Reach-1         , 2
Up Type= 0
Dn Type= 3
Dn Slope=0.00105
Boundary for River Rch & Prof#=SALUDA RIVER,Reach-1         , 3
Up Type= 0
Dn Type= 3
Dn Slope=0.00105
Boundary for River Rch & Prof#=SALUDA RIVER,Reach-1         , 4
Up Type= 0
Dn Type= 3
Dn Slope=0.00105
Boundary for River Rch & Prof#=SALUDA RIVER,Reach-1         , 5
Up Type= 0
Dn Type= 3
Dn Slope=0.00105
DSS Import GetInterval= 0
DSS Import GetPeak= 0
DSS Import FillOption= 0

--- CCR_SALUDA_RIVER.f02 (steady flow) ---

Flow Title=Floodway
Program Version=6.10
Number of Profiles= 2
Profile Names=100-year,100-FW
River Rch & RM=SALUDA RIVER,Reach-1         ,37500
  105000  105000
River Rch & RM=SALUDA RIVER,Reach-1         ,18800
   58600   58600
Boundary for River Rch & Prof#=SALUDA RIVER,Reach-1         , 1
Up Type= 0
Dn Type= 3
Dn Slope=0.00105
Boundary for River Rch & Prof#=SALUDA RIVER,Reach-1         , 2
Up Type= 0
Dn Type= 3
Dn Slope=0.00105
DSS Import GetInterval= 0
DSS Import GetPeak= 0
DSS Import FillOption= 0

--- CCR_SALUDA_RIVER.f03 (steady flow) ---

Flow Title=Multiple_Full Model
Program Version=6.10
Number of Profiles= 4
Profile Names=10-year,50-year,100-year,500-year
River Rch & RM=SALUDA RIVER,Reach-1         ,37500
   32000   90000  105000  145000
River Rch & RM=SALUDA RIVER,Reach-1         ,18800
   29600   48300   58600   89900
Boundary for River Rch & Prof#=SALUDA RIVER,Reach-1         , 1
Up Type= 0
Dn Type= 3
Dn Slope=0.00105
Boundary for River Rch & Prof#=SALUDA RIVER,Reach-1         , 2
Up Type= 0
Dn Type= 3
Dn Slope=0.00105
Boundary for River Rch & Prof#=SALUDA RIVER,Reach-1         , 3
Up Type= 0
Dn Type= 3
Dn Slope=0.00105
Boundary for River Rch & Prof#=SALUDA RIVER,Reach-1         , 4
Up Type= 0
Dn Type= 3
Dn Slope=0.00105
Observed WS=SALUDA RIVER    ,Reach-1         ,11000   ,,,,,
DSS Import GetInterval= 0
DSS Import GetPeak= 0
DSS Import FillOption= 0

--- CCR_SALUDA_RIVER.f04 (steady flow) ---

Flow Title=67kFlow
Program Version=5.07
Number of Profiles= 1
Profile Names=67k Flow
River Rch & RM=SALUDA RIVER,Reach-1         ,37500
   67000
Boundary for River Rch & Prof#=SALUDA RIVER,Reach-1         , 1
Up Type= 0
Dn Type= 3
Dn Slope=0.00105
DSS Import GetInterval= 0
DSS Import GetPeak= 0
DSS Import FillOption= 0

--- CCR_SALUDA_RIVER.f05 (steady flow) ---

Flow Title=FIS_GAGE_02169000_Upstream
Program Version=6.00
Number of Profiles= 5
Profile Names=10-year,50-year,100-year,500-year,67k
River Rch & RM=SALUDA RIVER,Reach-1         ,37500
   32000   90000  105000  145000   67000
Boundary for River Rch & Prof#=SALUDA RIVER,Reach-1         , 1
Up Type= 0
Dn Type= 3
Dn Slope=0.00105
Boundary for River Rch & Prof#=SALUDA RIVER,Reach-1         , 2
Up Type= 0
Dn Type= 3
Dn Slope=0.00105
Boundary for River Rch & Prof#=SALUDA RIVER,Reach-1         , 3
Up Type= 0
Dn Type= 3
Dn Slope=0.00105
Boundary for River Rch & Prof#=SALUDA RIVER,Reach-1         , 4
Up Type= 0
Dn Type= 3
Dn Slope=0.00105
Boundary for River Rch & Prof#=SALUDA RIVER,Reach-1         , 5
Up Type= 0
Dn Type= 3
Dn Slope=0.00105
Observed WS=SALUDA RIVER    ,Reach-1         ,11000   ,,,,,,
DSS Import GetInterval= 0
DSS Import GetPeak= 0
DSS Import FillOption= 0

--- CCR_SALUDA_RIVER.f06 (steady flow) ---

Flow Title=Richland_Flows
Program Version=6.00
Number of Profiles= 5
Profile Names=10-year,50-year,100-year,500-year,67k
River Rch & RM=SALUDA RIVER,Reach-1         ,37500
   29600   48300   58600   89900   67000
River Rch & RM=SALUDA RIVER,Reach-1         ,18580
   29600   48300   58600   89900   67000
Boundary for River Rch & Prof#=SALUDA RIVER,Reach-1         , 1
Up Type= 0
Dn Type= 3
Dn Slope=0.00105
Boundary for River Rch & Prof#=SALUDA RIVER,Reach-1         , 2
Up Type= 0
Dn Type= 3
Dn Slope=0.00105
Boundary for River Rch & Prof#=SALUDA RIVER,Reach-1         , 3
Up Type= 0
Dn Type= 3
Dn Slope=0.00105
Boundary for River Rch & Prof#=SALUDA RIVER,Reach-1         , 4
Up Type= 0
Dn Type= 3
Dn Slope=0.00105
Boundary for River Rch & Prof#=SALUDA RIVER,Reach-1         , 5
Up Type= 0
Dn Type= 3
Dn Slope=0.00105
Observed WS=SALUDA RIVER    ,Reach-1         ,11000   ,,,,,,
DSS Import GetInterval= 0
DSS Import GetPeak= 0
DSS Import FillOption= 0

--- CCR_SALUDA_RIVER.f07 (steady flow) ---

Flow Title=Lexington_Flows
Program Version=6.00
Number of Profiles= 5
Profile Names=10-year,50-year,100-year,500-year,67k
River Rch & RM=SALUDA RIVER,Reach-1         ,37500
   32000   90000  105000  145000   67000
River Rch & RM=SALUDA RIVER,Reach-1         ,18200
   29600   48300   58600   89900   67000
Boundary for River Rch & Prof#=SALUDA RIVER,Reach-1         , 1
Up Type= 0
Dn Type= 3
Dn Slope=0.00105
Boundary for River Rch & Prof#=SALUDA RIVER,Reach-1         , 2
Up Type= 0
Dn Type= 3
Dn Slope=0.00105
Boundary for River Rch & Prof#=SALUDA RIVER,Reach-1         , 3
Up Type= 0
Dn Type= 3
Dn Slope=0.00105
Boundary for River Rch & Prof#=SALUDA RIVER,Reach-1         , 4
Up Type= 0
Dn Type= 3
Dn Slope=0.00105
Boundary for River Rch & Prof#=SALUDA RIVER,Reach-1         , 5
Up Type= 0
Dn Type= 3
Dn Slope=0.00105
Observed WS=SALUDA RIVER    ,Reach-1         ,11000   ,,,,,,
DSS Import GetInterval= 0
DSS Import GetPeak= 0
DSS Import FillOption= 0

--- CCR_SALUDA_RIVER.f08 (steady flow) ---

Flow Title=Sensitivity_Analysis
Program Version=6.10
Number of Profiles= 3
Profile Names=-3,+0,+3
River Rch & RM=SALUDA RIVER,Reach-1         ,37500
  105000  105000  105000
River Rch & RM=SALUDA RIVER,Reach-1         ,18800
   58600   58600   58600
Boundary for River Rch & Prof#=SALUDA RIVER,Reach-1         , 1
Up Type= 0
Dn Type= 1
Dn Known WS=141.88
Boundary for River Rch & Prof#=SALUDA RIVER,Reach-1         , 2
Up Type= 0
Dn Type= 1
Dn Known WS=144.88
Boundary for River Rch & Prof#=SALUDA RIVER,Reach-1         , 3
Up Type= 0
Dn Type= 1
Dn Known WS=147.88
Observed WS=SALUDA RIVER    ,Reach-1         ,11000   ,,,,,,
DSS Import GetInterval= 0
DSS Import GetPeak= 0
DSS Import FillOption= 0

--- CCR_SALUDA_RIVER.f09 (steady flow) ---

Flow Title=Overtopping
Program Version=6.00
Number of Profiles= 5
Profile Names=10-year,50-year,100-year,500-year,67k
River Rch & RM=SALUDA RIVER,Reach-1         ,37500
  150000  175000  200000  225000  250000
Boundary for River Rch & Prof#=SALUDA RIVER,Reach-1         , 1
Up Type= 0
Dn Type= 3
Dn Slope=0.00105
Boundary for River Rch & Prof#=SALUDA RIVER,Reach-1         , 2
Up Type= 0
Dn Type= 3
Dn Slope=0.00105
Boundary for River Rch & Prof#=SALUDA RIVER,Reach-1         , 3
Up Type= 0
Dn Type= 3
Dn Slope=0.00105
Boundary for River Rch & Prof#=SALUDA RIVER,Reach-1         , 4
Up Type= 0
Dn Type= 3
Dn Slope=0.00105
Boundary for River Rch & Prof#=SALUDA RIVER,Reach-1         , 5
Up Type= 0
Dn Type= 3
Dn Slope=0.00105
Observed WS=SALUDA RIVER    ,Reach-1         ,11000   ,,,,,,
DSS Import GetInterval= 0
DSS Import GetPeak= 0
DSS Import FillOption= 0

--- CCR_SALUDA_RIVER.f10 (steady flow) ---

Flow Title=SCDOT_Multiple_Full Model
Program Version=6.10
Number of Profiles= 5
Profile Names=10-year,50-year,100-year,500-year,67k CFS
River Rch & RM=SALUDA RIVER,Reach-1         ,37500
   32000   90000  105000  145000   67000
River Rch & RM=SALUDA RIVER,Reach-1         ,18800
   29600   48300   58600   89900   67000
Boundary for River Rch & Prof#=SALUDA RIVER,Reach-1         , 1
Up Type= 0
Dn Type= 3
Dn Slope=0.00105
Boundary for River Rch & Prof#=SALUDA RIVER,Reach-1         , 2
Up Type= 0
Dn Type= 3
Dn Slope=0.00105
Boundary for River Rch & Prof#=SALUDA RIVER,Reach-1         , 3
Up Type= 0
Dn Type= 3
Dn Slope=0.00105
Boundary for River Rch & Prof#=SALUDA RIVER,Reach-1         , 4
Up Type= 0
Dn Type= 3
Dn Slope=0.00105
Observed WS=SALUDA RIVER    ,Reach-1         ,11000   ,,,,,,
DSS Import GetInterval= 0
DSS Import GetPeak= 0
DSS Import FillOption= 0

--- CCR_SALUDA_RIVER.g01 (geometry) ---

Geom Title=Scour
Program Version=6.10

River Reach=SALUDA RIVER    ,Reach-1
Reach XY= 30
        1940025.         809925.        1940425.         809275.
        1942325.         809075.        1942475.         808425.
        1943525.         808125.        1943875.         806525.
        1944475.         805775.        1944925.         806175.
        1945125.         805675.        1947525.         805825.
        1949375.         805175.        1952275.         801725.
        1954275.         800225.        1956175.         799775.
        1959675.         798025.        1962125.         797475.
        1962675.         796975.        1965325.         796925.
        1966075.         797275.        1967025.         796875.
        1969399.        797092.6      1970231.69       795104.72
      1971830.25       793650.36      1972881.79       793200.27
      1973823.05        793375.8      1975820.27       792485.86
      1977760.18       790682.11      1979514.91       791579.55
      1980277.87       791410.79      1981693.76        789580.3

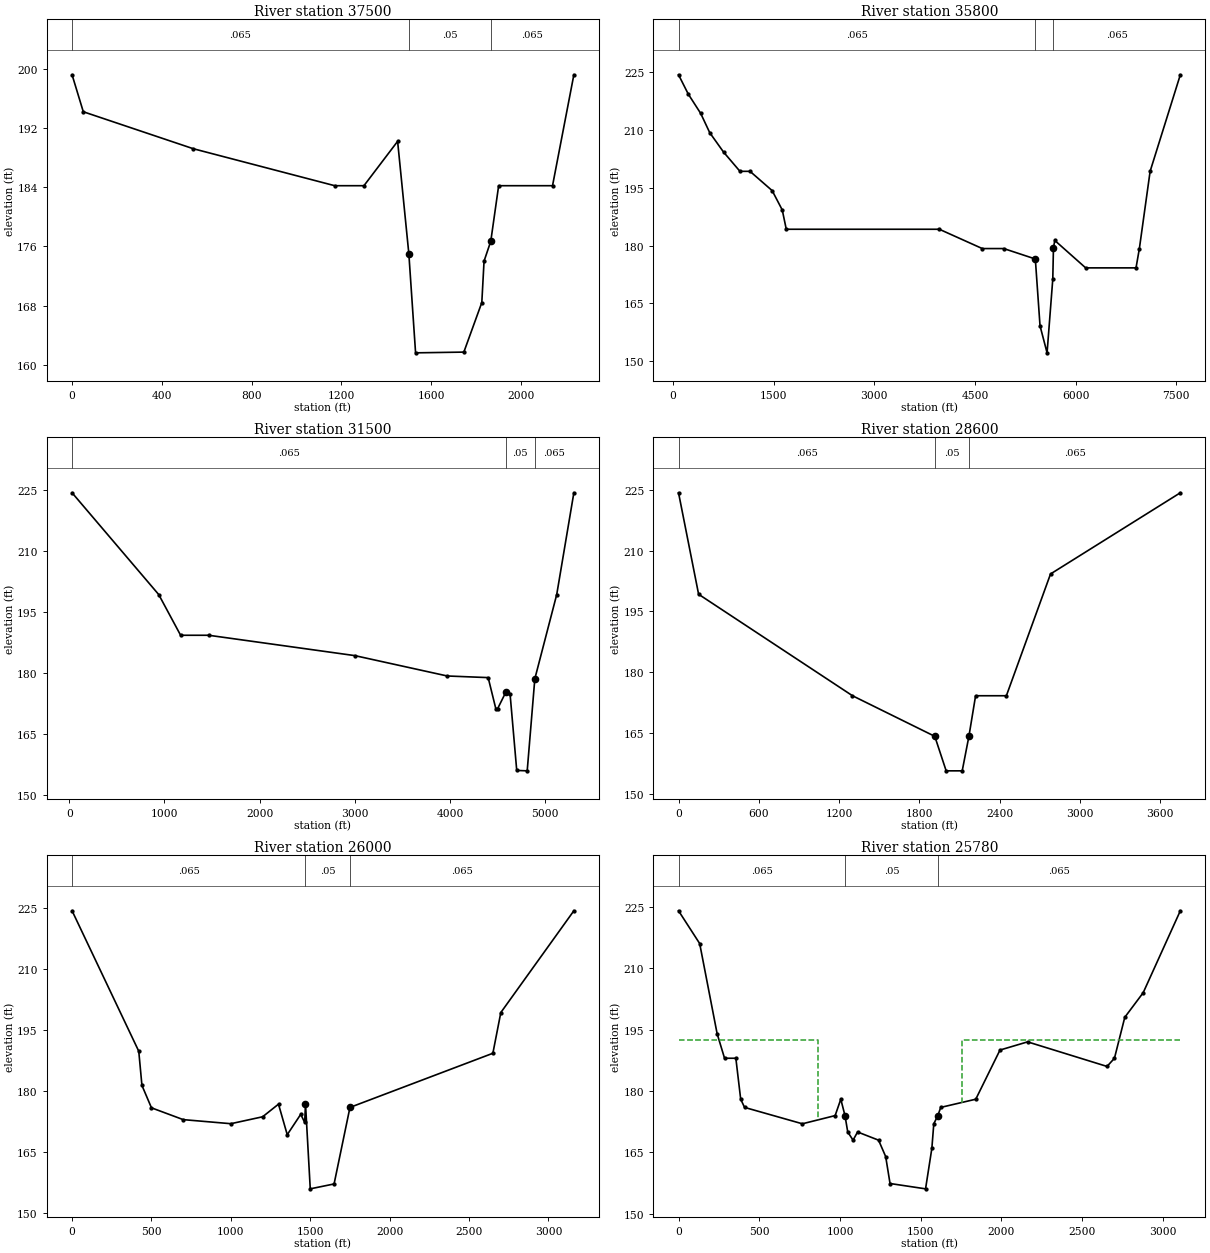
Type RM Length L Ch R = 1 ,37500   ,1700,1700,1700
BEGIN DESCRIPTION:
FEMA XS: O
END DESCRIPTION:
XS GIS Cut Line= 2
     1952046.143      804353.213     1950260.573      802133.301
#Sta/Elev= 15
       0  199.22      50  194.22     540  189.22    1170  184.22    1300  184.22
    1450  190.22    1500  175.02    1530  161.62    1745  161.72    1825  168.42
    1835  174.02    1865  176.72    1900  184.22    2140  184.22    2235  199.22
#Mann= 3 ,0,0
       0    .065       0    1500     .05       0    1865    .065       0
Bank Sta=1500,1865
XS Rating Curve= 0 ,0
Exp/Cntr=0.3,0.1

Type RM Length L Ch R = 1 ,35800   ,4100,4300,4400
BEGIN DESCRIPTION:
FEMA XS: N
END DESCRIPTION:
XS GIS Cut Line= 3
     1953019.318      804580.042     1953574.619      802890.459
     1950104.282      800182.426
#Sta/Elev= 24
      85  224.22     230  219.22     415  214.22     550  209.22     755  204.22
    1000  199.22    1150  199.22    1480  194.22    1630  189.22    1690  184.22
    3970  184.22    4610  179.22    4930  179.22    5400  176.52    5470  159.22
    5575  152.22    5660  171.32    5670  179.42    5690  181.32    6150  174.22
    6900  174.22    6950  179.22    7110  199.22    7560  224.22
#Mann= 3 ,0,0
      85    .065       0    5400     .05       0    5670    .065       0
Bank Sta=5400,5670
XS Rating Curve= 0 ,0
Exp/Cntr=0.3,0.1

Type RM Length L Ch R = 1 ,31500   ,2900,2900,2900
BEGIN DESCRIPTION:
FEMA XS: M
END DESCRIPTION:
XS GIS Cut Line= 2
     1956547.939      802894.387     1955359.257      798968.257
#Sta/Elev= 16
      30  224.22     940  199.22    1170  189.22    1465  189.22    3000  184.22
    3970  179.22    4400  178.82    4480  171.22    4500  171.22    4585  175.22
    4630  174.82    4700  156.02    4810  155.92    4890  178.52    5120  199.22
    5300  224.22
#Mann= 3 ,0,0
      30    .065       0    4585     .05       0    4890    .065       0
Bank Sta=4585,4890
XS Rating Curve= 0 ,0
Exp/Cntr=0.3,0.1

Type RM Length L Ch R = 1 ,28600   ,2600,2600,2600
BEGIN DESCRIPTION:
FEMA XS: L
END DESCRIPTION:
XS GIS Cut Line= 2
     1959299.258      800453.524     1957901.124      798273.368
#Sta/Elev= 11
       0  224.22     150  199.22    1300  174.22    1915  164.22    2000  155.72
    2120  155.72    2170  164.22    2220  174.22    2450  174.22    2780  204.22
    3750  224.22
#Mann= 3 ,0,0
       0    .065       0    1915     .05       0    2170    .065       0
Bank Sta=1915,2170
XS Rating Curve= 0 ,0
Exp/Cntr=0.3,0.1

Type RM Length L Ch R = 1 ,26000   ,320,220,170
BEGIN DESCRIPTION:
FEMA XS: K
END DESCRIPTION:
XS GIS Cut Line= 2
     1961084.429      798807.229     1960388.625      796915.593
#Sta/Elev= 18
       0  224.22     420  189.72     440  181.32     500  175.82     700  172.92
    1000  171.92    1200  173.62    1300  176.72    1355  169.22    1440  174.22
    1465  172.22    1470  176.82    1500  155.92    1650  157.12    1750  175.92
    2650  189.22    2700  199.22    3160  224.22
#Mann= 3 ,0,0
       0    .065       0    1470     .05       0    1750    .065       0
Bank Sta=1470,1750
XS Rating Curve= 0 ,0
Exp/Cntr=0.5,0.3

Type RM Length L Ch R = 1 ,25780   ,344,344,344
BEGIN DESCRIPTION:
New Section US I-20
END DESCRIPTION:
XS GIS Cut Line= 2
     1961666.693      798416.499     1960345.534      796994.429
#Sta/Elev= 30
       0     224     131     216     239     194     285     188     355     188
     385     178     409     176     767     172     970     174    1005     178
    1031     174    1048     170    1081     168    1109     170    1239     168
    1283     164    1310  157.42    1530  156.12    1569     166    1581     172
    1606     174    1624     176    1841     178    1991     190    2162     192
    2654     186    2700     188    2764     198    2878     204    3108     224
#Mann= 3 ,0,0
       0    .065       0    1031     .05       0    1606    .065       0
#XS Ineff= 2 , 0
       0   866.1  192.37  1753.8       0  192.37
Permanent Ineff=
       F       F
Bank Sta=1031,1606
XS Rating Curve= 0 ,0
Exp/Cntr=0.5,0.3

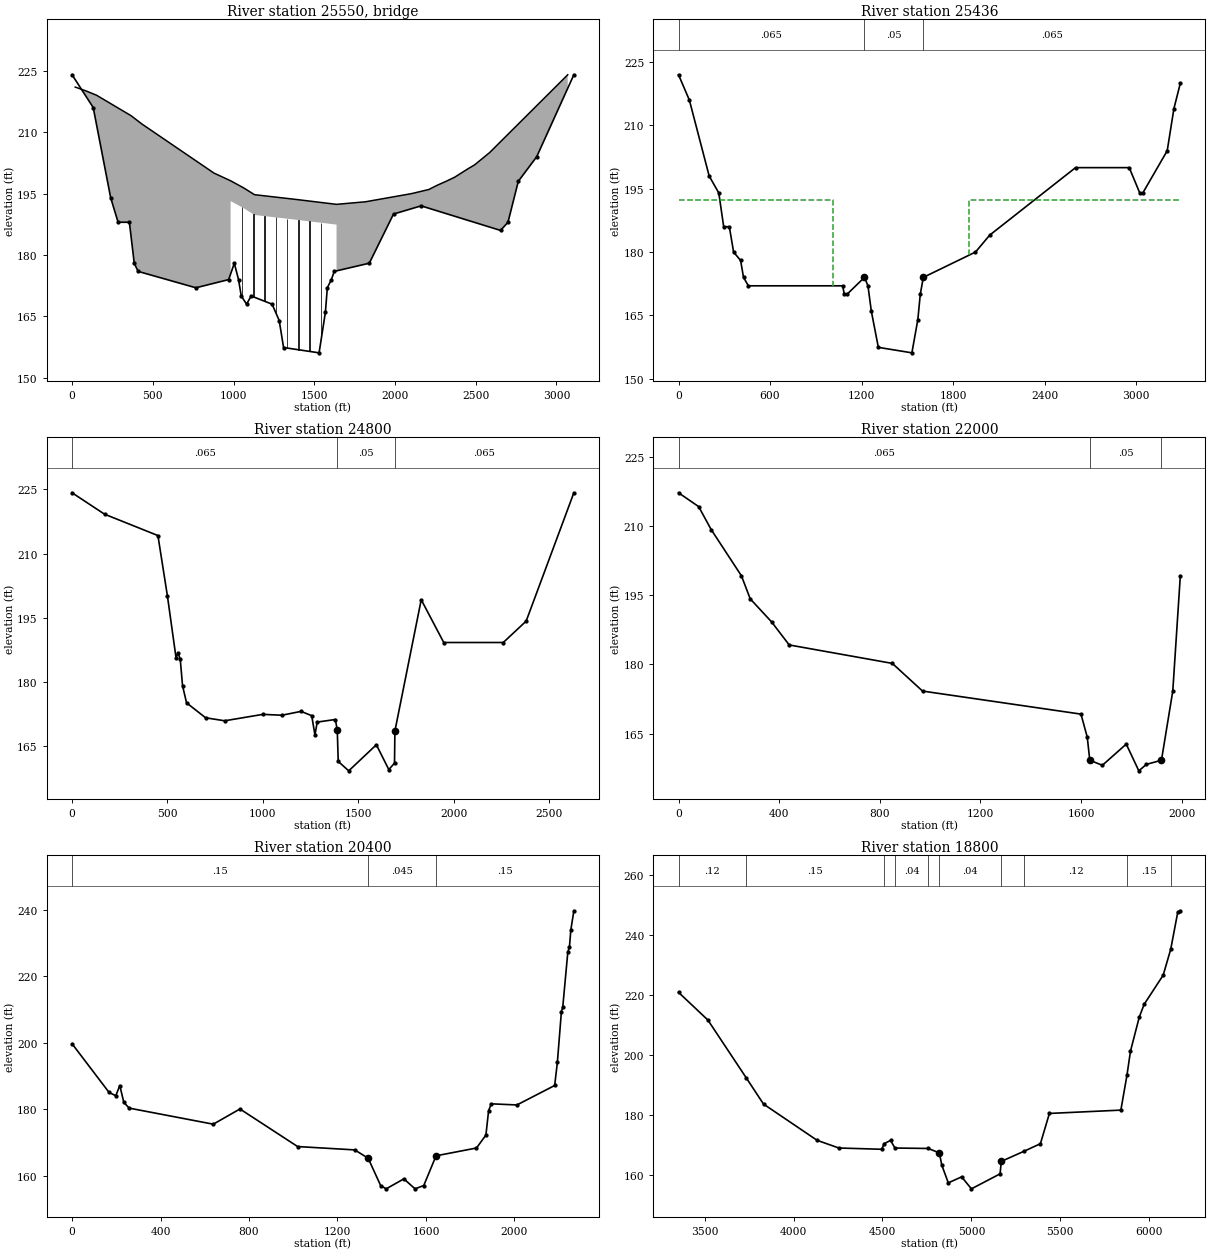
Type RM Length L Ch R = 3 ,25550   ,,,
Bridge Culvert--1,0,-1,-1, 0
Deck Dist Width WeirC Skew NumUp NumDn MinLoCord MaxHiCord MaxSubmerge Is_Ogee
95,108,2.5,0, 25, 26, 191.32, , 0.98, 0, 5.8,5.8,,
    19.5    90.2     152     366     399     432     879     982     982    1061
    1130    1391    1638    1638  1817.7    2104    2210    2260    2317    2370
    2410    2450    2493    2586    3070
     221     220     219     214     213     212     200 198.123 198.123 196.426
  194.73  193.55  192.37  192.37     193     195     196     197     198     199
     200     201     202     205     224
                                                                 193.173 191.476
  189.78   188.6  187.42
                                        
       0   167.5   238.2     300     514     547     580    1027    1130    1130
    1209    1278    1539    1786    1786  1965.7    2252    2358    2408    2465
    2518    2558    2598    2641    2734    3218
     222     221     220     219     214     213     212     200 198.123 198.123
 196.426  194.73  193.55  192.37  192.37     193     195     196     197     198
     199     200     201     202     205     224
                                                                         193.173
 191.476  189.78   188.6  187.42
                                                
Pier Skew, UpSta & Num, DnSta & Num=  ,1052, 2 ,1200, 2 , 0 , 0 , 0 ,,
     3.5     3.5
   156.9   192.2
     3.5     3.5
   156.9   192.2
Pier Skew, UpSta & Num, DnSta & Num=  ,1122, 2 ,1270, 2 , 0 , 0 , 0 ,,
     3.5     3.5
   156.9   192.2
     3.5     3.5
   156.9   192.2
Pier Skew, UpSta & Num, DnSta & Num=  ,1192, 2 ,1340, 2 , 0 , 0 , 0 ,,
     3.5     3.5
   156.9   192.2
     3.5     3.5
   156.9   192.2
Pier Skew, UpSta & Num, DnSta & Num=  ,1262, 2 ,1410, 2 , 0 , 0 , 0 ,,
     3.5     3.5
   156.9 193.173
     3.5     3.5
   156.9   192.2
Pier Skew, UpSta & Num, DnSta & Num=  ,1332, 2 ,1480, 2 , 0 , 0 , 0 ,,
     3.5     3.5
   156.9   192.2
     3.5     3.5
   156.9   192.2
Pier Skew, UpSta & Num, DnSta & Num=  ,1402, 2 ,1550, 2 , 0 , 0 , 0 ,,
     3.5     3.5
   156.9   192.2
     3.5     3.5
   156.9   192.2
Pier Skew, UpSta & Num, DnSta & Num=  ,1472, 2 ,1620, 2 , 0 , 0 , 0 ,,
     3.5     3.5
   156.9   192.2
     3.5     3.5
   156.9   192.2
Pier Skew, UpSta & Num, DnSta & Num=  ,1542, 2 ,1690, 2 , 0 , 0 , 0 ,,
     3.5     3.5
   156.9   192.2
     3.5     3.5
   156.9   192.2
Abutment Skew #Up #Dn= , 3 , 3
     982     986    1020
 191.173 191.173 174.173
    1130    1134    1168
 191.173 191.173 174.173
Abutment Skew #Up #Dn= , 3 , 3
    1542    1634    1638
  139.42  185.42  185.42
    1692    1784    1786
  139.42  185.42  185.42
BR Coef= 0 , 0 , 1 ,1.25, 0 ,,,0.8,0,,2,
WSPro=,,,, 1 ,,,, 0 ,,,, 0 ,,,,-1 ,-1 ,-1 , 0 , 0 , 0 , 0 , 0
BC Design=,, 0 ,, 0 ,,,,,,
BC Use User HTab Curves=0
BC User HTab FreeFlow(D)= 0

Type RM Length L Ch R = 1 ,25436   ,636,636,636
BEGIN DESCRIPTION:
New Section DS of I-20
END DESCRIPTION:
XS GIS Cut Line= 2
     1961813.217      798280.372     1960492.059      796858.302
#Sta/Elev= 30
       0     222      71     216     201     198     264     194     296     186
     333     186     361     180     407     178     426     174     458     172
    1076     172    1087     170    1105     170    1219     174    1242     172
    1264     166    1310  157.42    1530  156.12    1569     164    1585     170
    1605     174    1947     180    2040     184    2603     200    2955     200
    3024     194    3044     194    3204     204    3248     214    3290     220
#Mann= 3 ,0,0
       0    .065       0    1219     .05       0    1605    .065       0
#XS Ineff= 2 , 0
       0  1014.1  192.37  1901.8       0  192.37
Permanent Ineff=
       F       F
Bank Sta=1219,1605
XS Rating Curve= 0 ,0
Exp/Cntr=0.5,0.3

Type RM Length L Ch R = 1 ,24800   ,2800,2800,2800
BEGIN DESCRIPTION:
FEMA XS: J
END DESCRIPTION:
XS GIS Cut Line= 2
     1962086.565       798384.88     1961565.785      796319.252
#Sta/Elev= 30
       0  224.22     170  219.22     450  214.22     500  200.02     545  185.62
     555  186.82     567  185.32     579  179.12     600  175.12     700  171.62
     800  170.92    1000  172.42    1100  172.22    1200  173.12    1256  172.12
    1273  167.62    1285  170.62    1380  171.22    1390  168.72    1395  161.42
    1450  159.22    1595  165.32    1660  159.52    1690  161.02    1692  168.52
    1830  199.22    1948  189.22    2260  189.22    2380  194.22    2630  224.22
#Mann= 3 ,0,0
       0    .065       0    1390     .05       0    1692    .065       0
Bank Sta=1390,1692
XS Rating Curve= 0 ,0
Exp/Cntr=0.5,0.3

Type RM Length L Ch R = 1 ,22000   ,1600,1600,1600
BEGIN DESCRIPTION:
FEMA XS: I
END DESCRIPTION:
XS GIS Cut Line= 2
     1964713.343      798155.587     1964453.567      796811.327
#Sta/Elev= 19
       0  217.22      80  214.22     130  209.22     250  199.22     285  194.22
     370  189.22     440  184.22     850  180.22     970  174.22    1600  169.22
    1625  164.22    1635  159.22    1685  158.12    1780  162.72    1830  156.92
    1860  158.32    1920  159.22    1965  174.22    1995  199.22
#Mann= 3 ,0,0
       0    .065       0    1635     .05       0    1920    .065       0
Bank Sta=1635,1920
XS Rating Curve= 0 ,0
Exp/Cntr=0.3,0.1

Type RM Length L Ch R = 1 ,20400   ,1600,1600,1600
XS GIS Cut Line= 4
      1966617.13       798553.45      1966464.72       797189.02
      1966446.58       796913.23      1966337.72       796303.59
#Sta/Elev= 30
       0  199.67  167.07  185.04  197.67  184.02  215.78   187.1   233.9  182.04
  258.04   180.3   638.4  175.46  759.01  180.04 1019.69  168.73 1278.35  167.72
 1338.72   165.2    1395     157    1420     156    1500     159  1550.7     156
    1590     157 1645.52  165.94 1828.32  168.29 1870.98  172.18 1883.17  179.55
 1895.36  181.59 2011.14  181.25 2181.82  187.11 2194.01  194.05  2212.3  209.38
 2218.39  210.71 2241.22  227.23 2248.64  228.81 2254.96  233.97 2268.58   239.7
#Mann= 3 ,0,0
       0     .15       0 1338.72    .045       0 1645.52     .15       0
Bank Sta=1338.72,1645.52
XS Rating Curve= 0 ,0
Exp/Cntr=0.3,0.1

Type RM Length L Ch R = 1 ,18800   ,600,600,600
BEGIN DESCRIPTION:
SALUDA RIVER 45.0
END DESCRIPTION:
XS GIS Cut Line= 3
      1967994.19       798504.51        1967652.       796893.35
      1967253.26       795788.08
#Sta/Elev= 30
  3352.9  220.87  3517.8  211.64  3733.9  192.32  3830.8  183.59  4132.3  171.49
  4254.4  168.93  4495.5   168.5  4509.4  170.37  4545.2  171.47    4570  168.92
  4757.1  168.77    4820   167.3    4833   163.3    4870   157.3    4945   159.3
    5000   155.3  5161.3   160.3  5168.1  164.46  5295.1  167.82  5388.1  170.36
  5438.6  180.46  5840.6  181.57  5875.2  193.34  5894.7  201.26  5943.8  212.54
  5971.3  216.85  6078.6   226.6  6120.9  235.23  6160.4  247.58    6175  248.09
#Mann= 10 ,-1,0
  3352.9     .12       0  3733.9     .15       0  4509.4     .08       0
    4570     .04       0  4757.1     .15       0    4820     .04       0
  5168.1     .15       0  5295.1     .12       0  5875.2     .15       0
  6120.9     .12       0
Bank Sta=4820,5168.1
XS Rating Curve= 0 ,0
Exp/Cntr=0.3,0.1