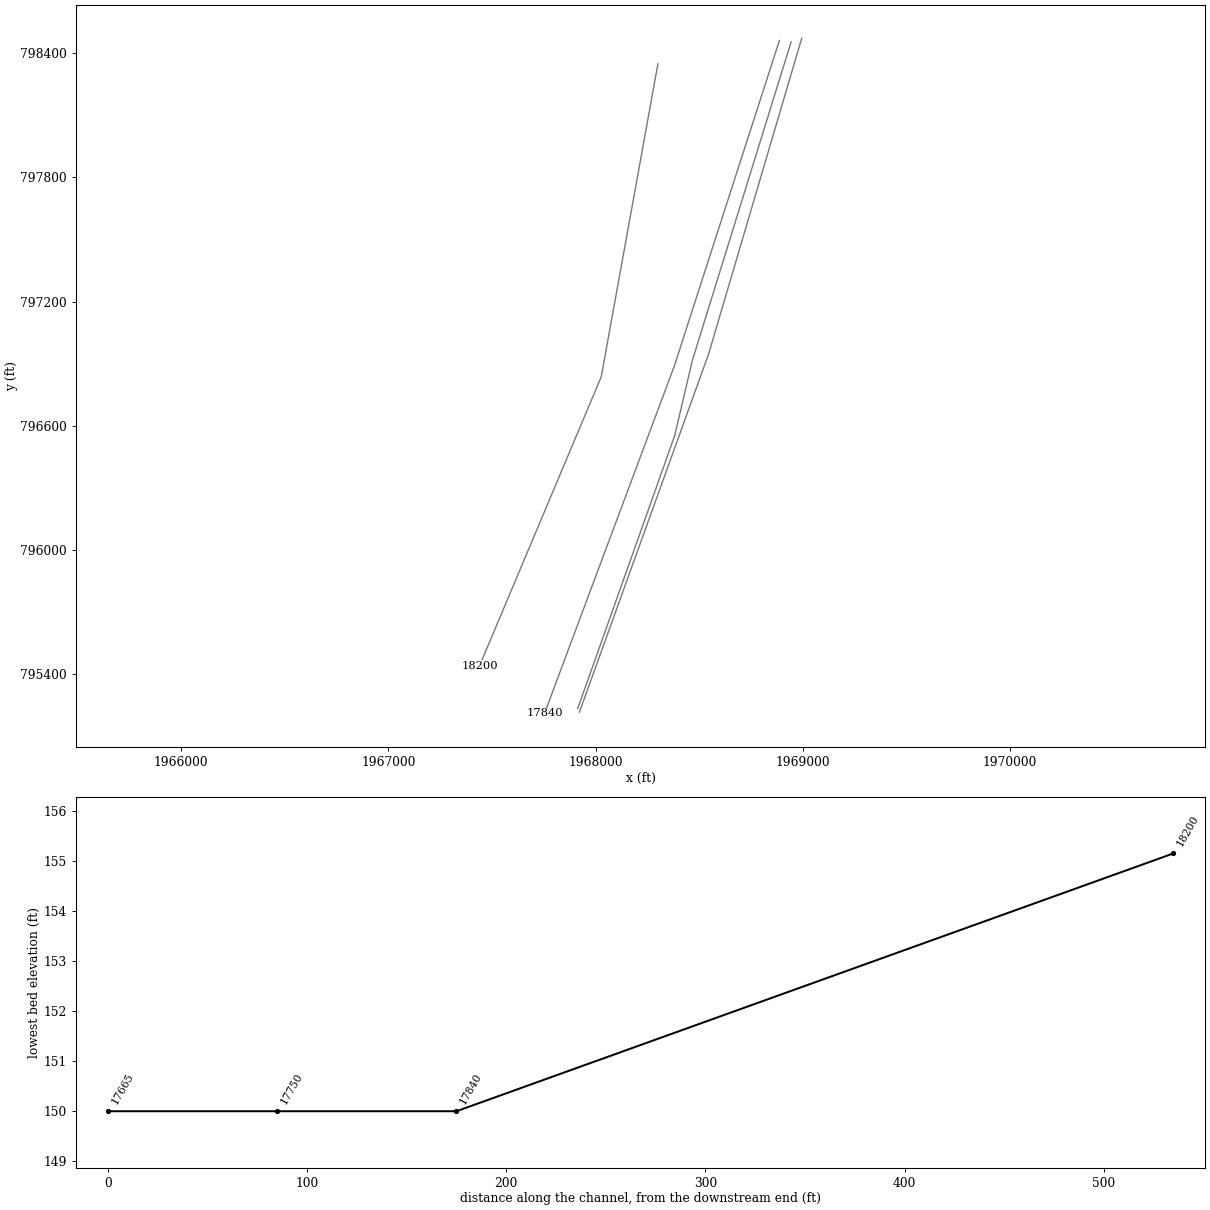
HEC-RAS study CCR_SALUDA_RIVER.prj: CCR SALUDA RIVER Detailed Study

--- CCR_SALUDA_RIVER.g01 (geometry) --- (continued)

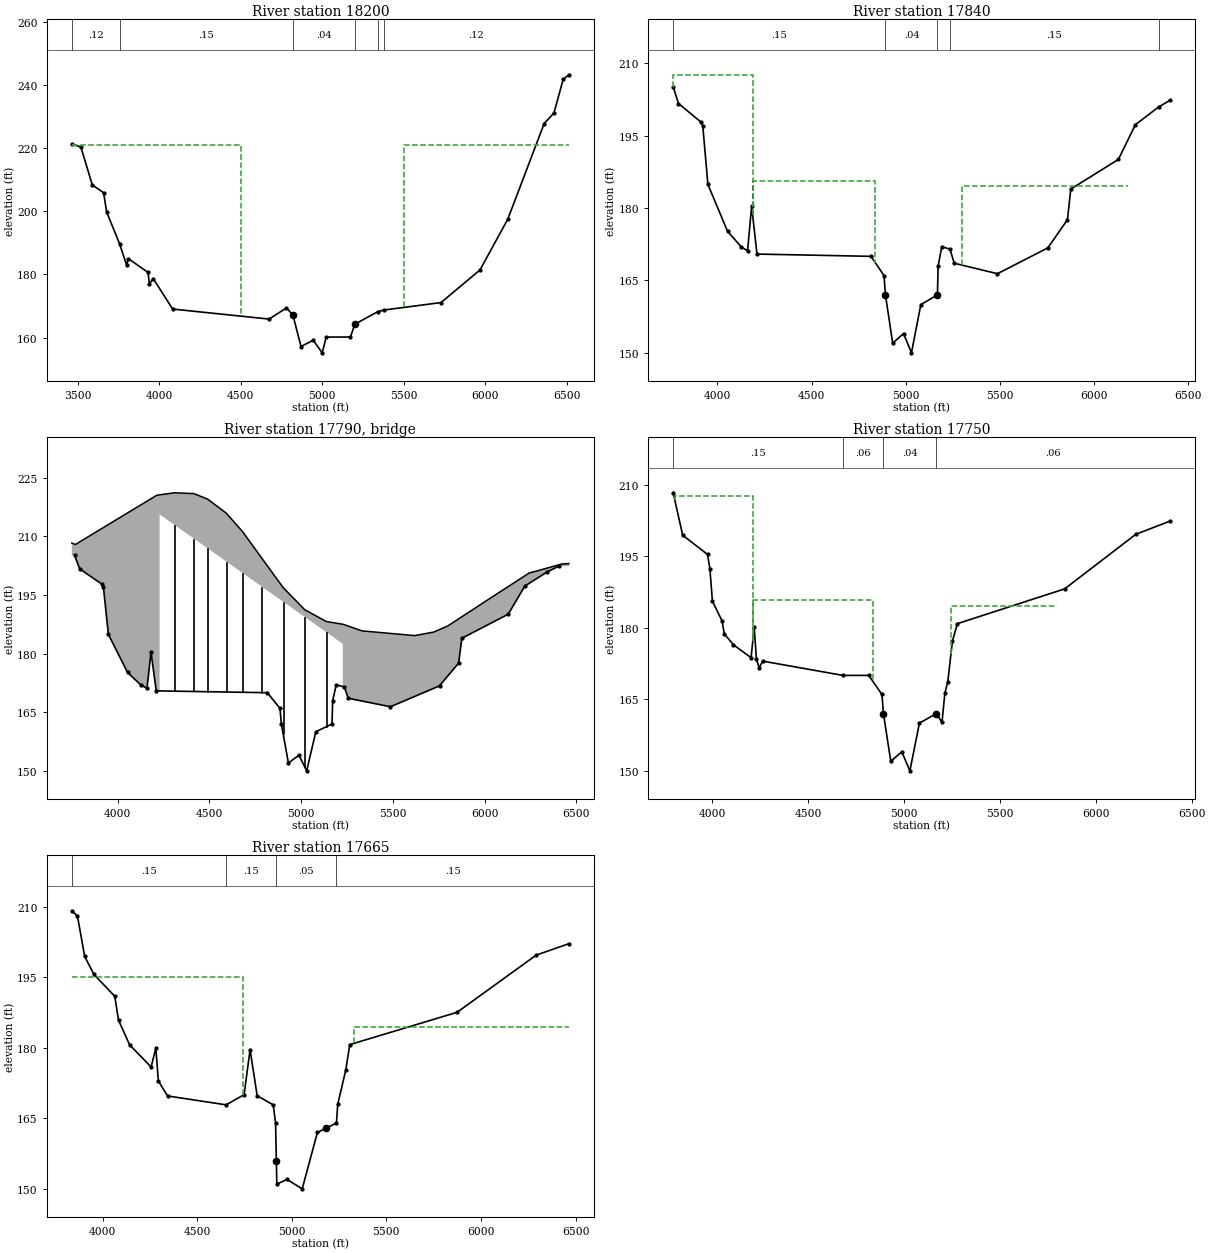
Type RM Length L Ch R = 1 ,18200   ,399,360,425
BEGIN DESCRIPTION:
SALUDA RIVER 44.0
END DESCRIPTION:
XS GIS Cut Line= 3
      1968300.98       798348.76      1968027.38       796836.81
      1967440.11       795441.03
#Sta/Elev= 30
  3463.5   221.2  3518.9  220.41    3589  208.36  3658.5  205.88  3677.1   199.8
    3757  189.63  3800.2  182.87  3809.3  185.04  3931.2  180.63  3939.6  176.98
  3962.8  178.68  4082.2  169.03  4674.2  165.86  4780.6  169.39    4820  167.16
    4870  157.16    4945  159.16    5000  155.16  5024.7  160.16  5173.5  160.17
  5199.8  164.22  5340.1  168.17  5377.5  168.72  5729.2  171.09  5968.2  181.42
  6138.8   197.5  6361.9  227.77  6422.4   231.2    6479  241.85  6514.3  243.26
#Mann= 6 ,-1,0
  3463.5     .12       0    3757     .15       0    4820     .04       0
  5199.8     .15       0  5340.1     .04       0  5377.5     .12       0
#XS Ineff= 2 , 0
       0    4500     221    5500       0     221
Permanent Ineff=
       F       F
Bank Sta=4820,5199.8
XS Rating Curve= 0 ,0
Exp/Cntr=0.5,0.3

Type RM Length L Ch R = 1 ,17840   ,77,90,170
BEGIN DESCRIPTION:
SALUDA RIVER (I-26 Ramp - US)
END DESCRIPTION:
XS GIS Cut Line= 3
       1968887.4       798461.11      1968380.66       796890.12
      1967753.47       795210.18
#Sta/Elev= 30
 3765.71  205.13 3793.98  201.67 3916.01  197.74 3922.91  197.01 3949.95  184.91
 4054.36  175.18 4128.21  171.92 4160.38  171.14 4182.13   180.4 4210.55  170.47
 4815.73     170 4884.67     166 4892.33     162 4930.64     152 4988.09     154
 5030.22     150 5080.01     160 5168.11     162 5171.94     168 5191.09     172
 5234.83  171.49 5257.12  168.57 5486.56   166.4 5753.83  171.75 5858.09  177.59
 5875.71  183.94 6128.12  190.08 6218.74  197.29 6342.15  200.96 6403.89  202.38
#Mann= 5 ,-1,0
 3765.71     .15       0 4892.33     .04       0 5168.11     .04       0
 5234.83     .15       0 6342.15     .11       0
#XS Ineff= 3 ,-1
 3727.95 4187.57  207.63 4187.65 4838.71   185.7 5298.34 6179.29  184.62
Permanent Ineff=
       F       F       F
Bank Sta=4892.33,5168.11
XS Rating Curve= 0 ,0
Skew Angle= 40
Exp/Cntr=0.5,0.3

Type RM Length L Ch R = 3 ,17790   ,,,
BEGIN DESCRIPTION:
SALUDA RIVER (I-26 Ramp - TOR)
Structure ID: I-26 Ramp
Detailed Survey Structure
END DESCRIPTION:
Bridge Culvert--1,0,-1,-1, 0
Deck Dist Width WeirC Skew NumUp NumDn MinLoCord MaxHiCord MaxSubmerge Is_Ogee
32.5,35,3,40, 25, 25, , , 0.95, 0, 1,1,,
3750.8513770.0024213.6964229.0164229.0164309.6814415.625 4490.854592.3514681.672
4785.0884902.2935019.4985136.7025227.0965227.0965230.9265331.9675618.3915722.573
5799.4086011.5256241.0326419.5976459.125
   208.3  207.93  220.54  220.64  220.64  221.17  220.96  219.54  215.95  211.19
  204.47   196.9  191.24  188.23  187.51  187.51  187.48  185.82  184.62  185.52
   187.1  193.61   200.6  202.94  203.05
                                  215.64  212.96  209.45  206.95  203.58  200.61
  197.18  193.29   189.4  185.51  182.51
                                        
3750.8513770.0024213.6964229.0164229.0164309.6814415.625 4490.854592.3514681.672
4785.0884902.2935019.4985136.7025227.0965227.0965230.9265331.9675618.3915722.573
5799.4086011.5256241.0326419.5976459.125
   208.3  207.93  220.54  220.64  220.64  221.17  220.96  219.54  215.95  211.19
  204.47   196.9  191.24  188.23  187.51  187.51  187.48  185.82  184.62  185.52
   187.1  193.61   200.6  202.94  203.05
                                  215.64  212.96  209.45  206.95  203.58  200.61
  197.18  193.29   189.4  185.51  182.51
                                        
Pier Skew, UpSta & Num, DnSta & Num=  ,4309.681, 2 ,4309.681, 2 , 0 , 0 , 0 ,0,0
       5       5
   194.5  212.96
       5       5
   194.5  212.96
Pier Skew, UpSta & Num, DnSta & Num=  ,4415.625, 2 ,4415.625, 2 , 0 , 0 , 0 ,0,0
       5       5
  192.72  209.45
       5       5
  192.72  209.45
Pier Skew, UpSta & Num, DnSta & Num=  ,4490.85, 2 ,4490.85, 2 , 0 , 0 , 0 ,0,0
       5       5
     177  206.95
       5       5
     177  206.95
Pier Skew, UpSta & Num, DnSta & Num=  ,4592.351, 2 ,4592.351, 2 , 0 , 0 , 0 ,0,0
       5       5
     168  203.58
       5       5
     168  203.58
Pier Skew, UpSta & Num, DnSta & Num=  ,4681.672, 2 ,4681.672, 2 , 0 , 0 , 0 ,0,0
       5       5
     168  200.62
       5       5
     168  200.62
Pier Skew, UpSta & Num, DnSta & Num=  ,4785.088, 2 ,4785.088, 2 , 0 , 0 , 0 ,0,0
       5       5
     168  197.18
       5       5
     168  197.18
Pier Skew, UpSta & Num, DnSta & Num=  ,4902.293, 2 ,4902.293, 2 , 0 , 0 , 0 ,0,0
       5       5
     156  193.29
       5       5
     156  193.29
Pier Skew, UpSta & Num, DnSta & Num=  ,5019.498, 2 ,5019.498, 2 , 0 , 0 , 0 ,0,0
       5       5
     150   189.4
       5       5
     150   189.4
Pier Skew, UpSta & Num, DnSta & Num=  ,5136.702, 2 ,5136.702, 2 , 0 , 0 , 0 ,0,0
       5       5
     160  185.51
       5       5
     160  185.51
BR Coef= 1 , 1 , 0 ,1.25, 0 ,,,0.8,0,2,0,
WSPro=,,,, 1 ,,,, 0 ,,,, 0 ,,,,-1 ,-1 ,-1 , 0 , 0 , 0 , 0 , 0
BC Design=,, 0 ,, 0 ,,,,,,
BC HTab HWMax=205.13
BC Use User HTab Curves=0
BC User HTab FreeFlow(D)= 0

Type RM Length L Ch R = 1 ,17750   ,67,85,34
BEGIN DESCRIPTION:
SALUDA RIVER (I-26 Ramp - DS)
END DESCRIPTION:
XS GIS Cut Line= 4
      1968944.07       798454.82      1968467.06       796915.33
      1968381.51       796550.92      1967913.41       795232.68
#Sta/Elev= 30
 3795.59  208.27 3845.23  199.38 3974.69  195.35  3987.1  192.33 4000.35  185.56
 4050.68  181.41 4062.09  178.72 4109.28  176.44 4201.98  173.71 4218.06  180.09
 4229.94  173.41 4244.87  171.54 4261.73     173 4681.06     170 4815.73     170
 4884.67     166 4892.33     162 4930.64     152 4988.09     154 5030.22     150
 5080.01     160 5168.11     162 5197.68  160.15    5213  166.36 5228.01  168.68
 5252.07  177.18 5277.88  180.84 5837.48  188.13 6208.63  199.57 6388.57  202.35
#Mann= 4 ,-1,0
 3795.59     .15       0 4681.06     .06       0 4892.33     .04       0
 5168.11     .06       0
#XS Ineff= 3 ,-1
 3804.55 4210.55  207.63 4210.63 4838.71   185.7 5244.33 5796.27  184.62
Permanent Ineff=
       F       F       F
Bank Sta=4892.33,5168.11
XS Rating Curve= 0 ,0
Skew Angle= 40
Exp/Cntr=0.5,0.3

Type RM Length L Ch R = 1 ,17665   ,285,285,285
BEGIN DESCRIPTION:
SALUDA RIVER (I-26 - US)
END DESCRIPTION:
XS GIS Cut Line= 3
      1968995.05       798471.57      1968545.83       796947.19
      1967921.81       795215.91
#Sta/Elev= 30
 3837.82  209.19 3867.32  208.12 3905.62  199.48 3954.65  195.63 4064.65  190.99
 4084.49  185.92 4142.86  180.68  4256.7  175.93 4281.75  179.95    4295  172.97
  4344.1  169.77 4653.43  167.88 4748.27  170.05 4779.75  179.64 4817.21  169.82
 4902.17  167.87 4914.58     164 4918.64 155.988 4921.16     151 4974.79     152
 5055.22     150 5135.66     162 5180.09 162.883 5236.31     164  5242.9     168
  5285.5  175.27 5306.49   180.7 5873.36  187.57 6291.77  199.75 6464.97  202.19
#Mann= 4 ,-1,0
 3837.82     .15       0 4653.43     .15       0 4914.58     .05       0
 5236.31     .15       0
#XS Ineff= 2 , 0
       0    4740   195.1 5328.32       0   184.5
Permanent Ineff=
       F       F
Bank Sta=4918.64,5180.09
XS Rating Curve= 0 ,0
Skew Angle= 40
Exp/Cntr=0.5,0.3