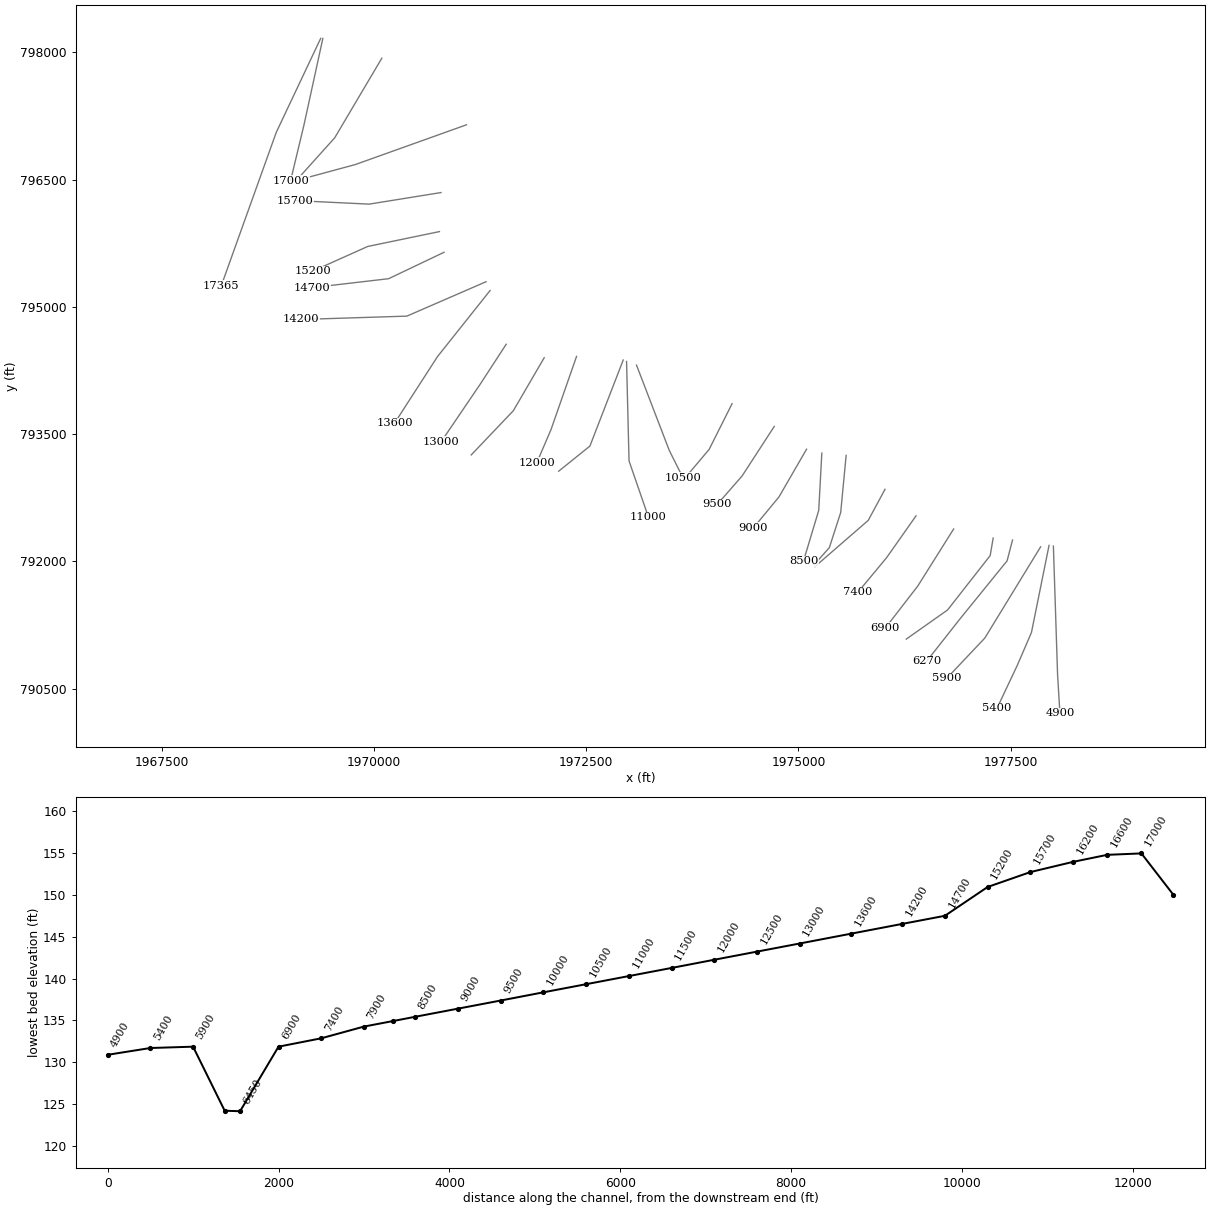
HEC-RAS study CCR_SALUDA_RIVER.prj: CCR SALUDA RIVER Detailed Study

--- CCR_SALUDA_RIVER.g01 (geometry) --- (continued)

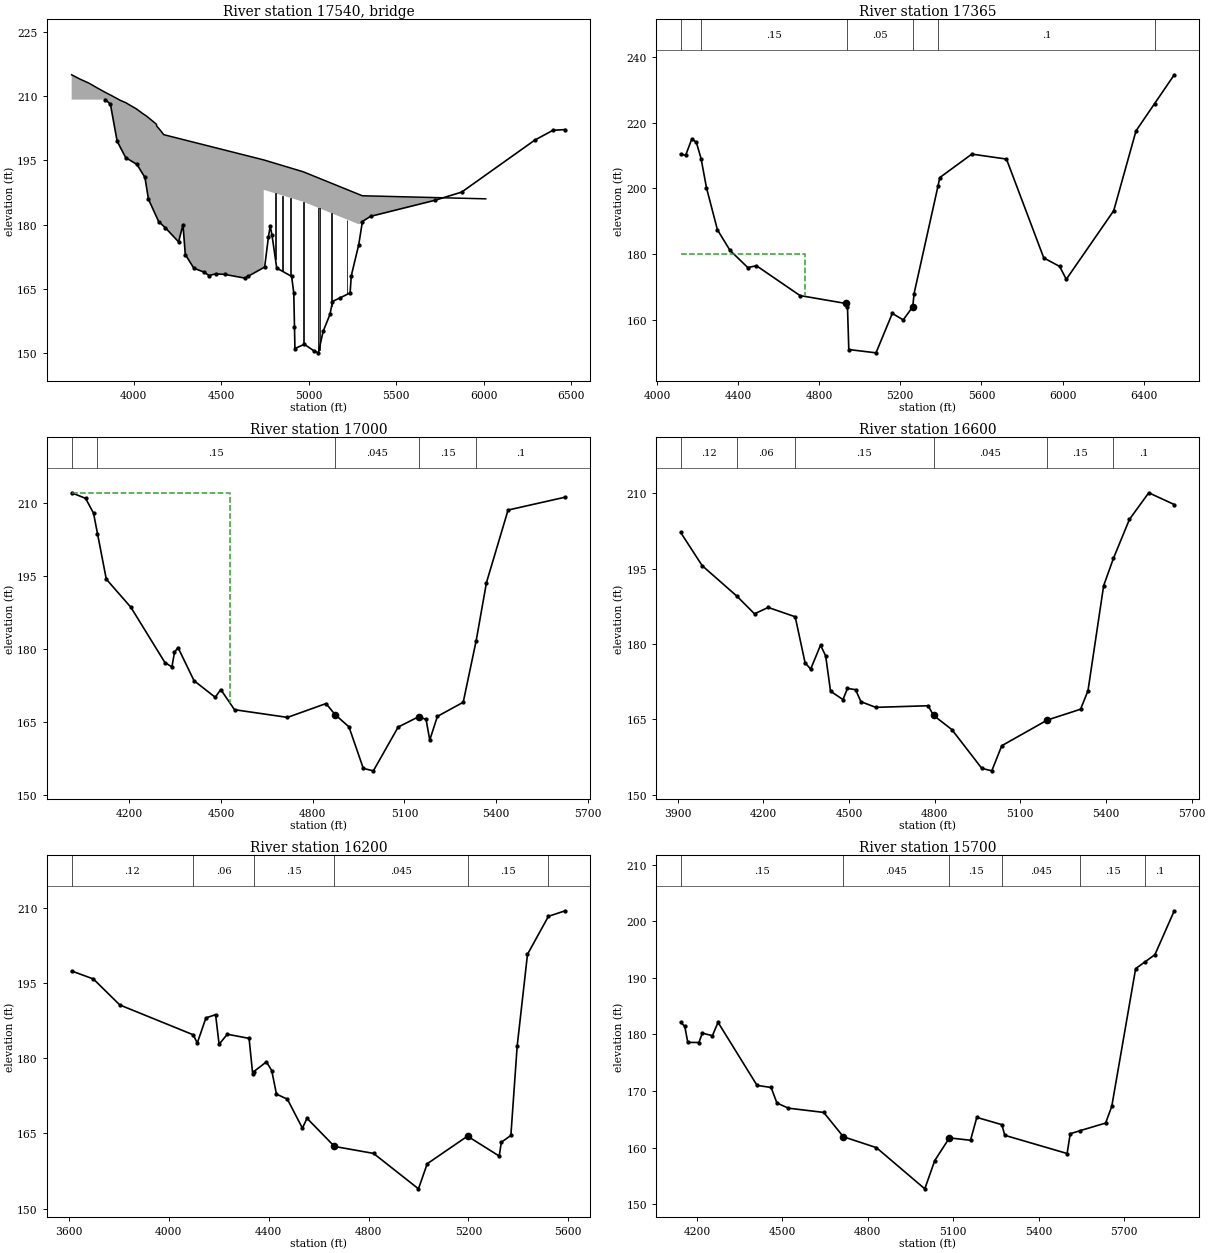
Type RM Length L Ch R = 3 ,17540   ,,,
BEGIN DESCRIPTION:
SALUDA RIVER (I-26 - TOR)
Structure ID: I-26
Detailed Survey Structure
END DESCRIPTION:
Bridge Culvert--1,0,-1,-1, 0
Deck Dist Width WeirC Skew NumUp NumDn MinLoCord MaxHiCord MaxSubmerge Is_Ogee
5,273,3,0, 22, 22, , , 0.95, 0, 2,2,,
    3646    3693    3747    3789    3833    3880    3925    3954    3980    4015
    4051    4074    4130    4132    4153    4172    4743    4743    4969    5306
    5306    6011
     215     214     213     212     211     210     209 208.497  207.87 207.048
 205.965 205.336 203.447     203     202     201   195.1   195.1  192.32  186.72
  186.72     186
                                                                                
                                                           188.1  185.32  179.72
                
    3646    3693    3747    3789    3833    3880    3925    3954    3980    4015
    4051    4074    4130    4132    4153    4172    4743    4743    4969    5306
    5306    6011
     215     214     213     212     211     210     209 208.497  207.87 207.048
 205.965 205.336 203.447     203     202     201   195.1   195.1  192.32  186.72
  186.72     186
                                                                                
                                                           188.1  185.32  179.72
                
Pier Skew, UpSta & Num, DnSta & Num=  ,4810, 2 ,4810, 2 , 0 , 0 , 0 ,,
       4       4
     150     190
       4       4
     150     190
Pier Skew, UpSta & Num, DnSta & Num=  ,4852, 2 ,4852, 2 , 0 , 0 , 0 ,,
       4       4
     150     190
       4       4
     150     190
Pier Skew, UpSta & Num, DnSta & Num=  ,4894, 2 ,4894, 2 , 0 , 0 , 0 ,,
       4       4
     150     190
       4       4
     150     190
Pier Skew, UpSta & Num, DnSta & Num=  ,4970.5, 2 ,4970.5, 2 , 0 , 0 , 0 ,,
     6.5     6.5
     150     190
     6.5     6.5
     150     190
Pier Skew, UpSta & Num, DnSta & Num=  ,5058.5, 2 ,5058.5, 2 , 0 , 0 , 0 ,,
     6.5     6.5
     150     190
     6.5     6.5
     150     190
Pier Skew, UpSta & Num, DnSta & Num=  ,5131, 2 ,5131, 2 , 0 , 0 , 0 ,,
     6.5     6.5
     150     190
     6.5     6.5
     150     190
Pier Skew, UpSta & Num, DnSta & Num=  ,5219, 2 ,5219, 2 , 0 , 0 , 0 ,,
       4       4
     150     190
       4       4
     150     190
Abutment Skew #Up #Dn= , 3 , 3
    4743    4745    4765
     185     185     175
    4743    4745    4765
     185     185     175
BR Coef= 1 , 1 , 0 ,1.25, 0 ,,,0.8,0,1.2,0,
WSPro=,,,, 1 ,,,, 0 ,,,, 0 ,,,,-1 ,-1 ,-1 , 0 , 0 , 0 , 0 , 0
BR U #Sta/Elev= 45
 3837.82  209.19 3867.32  208.12 3905.62  199.48 3954.65  195.63 4018.53  194.05
 4064.65  190.99 4084.49  185.92 4142.86  180.68 4180.94  179.24  4256.7  175.93
 4281.75  179.95    4295  172.97  4344.1  169.77 4400.87  168.89 4430.74  168.06
  4468.2  168.46 4519.53  168.34 4635.35  167.47 4653.43  167.88 4748.27  170.05
  4770.1  177.19 4779.75  179.64 4790.17  177.51 4817.21  169.82 4902.17  167.87
 4914.58     164 4918.64 155.988 4921.16     151 4974.79     152 5028.41   150.5
 5055.22     150 5082.03     155 5121.41     159 5135.66     162 5180.09 162.883
 5236.31     164  5242.9     168  5285.5  175.27 5306.49   180.7 5352.83   181.9
    5720  185.65 5873.36  187.57 6291.77  199.75 6395.42  202.03 6464.97  202.19
BR U #Mann= 4
 3837.82     .15 4653.43     .15 4914.58     .05 5236.31     .15
BR D #Sta/Elev= 30
    4000  226.35 4103.31  220.79 4184.08   214.7    4254  211.22 4258.98  210.11
 4592.87  193.51 4602.83  192.06 4777.25  186.19 4782.24  185.39 4802.17  170.19
 4812.14     167 4928.24   162.9 4962.96   150.3 5053.24   150.3 5081.02  156.71
 5181.29  164.02  5195.9  163.56 5243.93   167.6 5283.62  178.38 5307.99  183.06
 5332.35  181.92 5437.58  182.35 5507.94  185.31 5512.81  184.75 5522.59  185.88
 5532.46   185.4 5561.67  187.51 5586.09  186.78 5590.98  188.11 5757.07  185.11
BR D #Mann= 3
    4000     .15 4928.24     .05 5181.29     .15
BR D Banks=4928.24,5181.29
BC Design=,, 0 ,, 0 ,,,,,,
BC HTab HWMax=209.19
BC Use User HTab Curves=0
BC User HTab FreeFlow(D)= 0

Type RM Length L Ch R = 1 ,17365   ,296,375,406
BEGIN DESCRIPTION:
SALUDA RIVER (I-26 - DS)
END DESCRIPTION:
XS GIS Cut Line= 3
      1969374.07       798165.33      1968850.37       797056.55
      1968201.88        795246.1
#Sta/Elev= 30
 4117.23  210.41 4141.74  210.03 4171.46  214.91 4194.06  214.07 4217.73  209.05
 4244.47  200.17 4298.47  187.38 4360.37  181.15 4448.24  175.91 4490.67  176.48
 4705.47  167.41 4931.92     165 4939.58     164 4946.16     151 5080.22     150
 5160.66     162 5214.28     160 5261.31     164  5267.9     168 5386.03  200.73
 5394.76  203.27 5552.64   210.4 5723.47  208.89 5907.32  178.85 5985.69  176.26
 6018.24  172.35 6252.27  193.21 6362.04  217.46 6453.74  225.75 6550.65  234.51
#Mann= 6 ,-1,0
 4117.23     .06       0 4217.73     .15       0 4939.58     .05       0
 5261.31     .15       0 5386.03      .1       0 6453.74     .11       0
#XS Ineff= 2 , 0
       0 4730.52  180.12  5376.3       0   184.5
Permanent Ineff=
       F       F
Bank Sta=4931.92,5261.31
XS Rating Curve= 0 ,0
Skew Angle= 40
Exp/Cntr=0.5,0.3

Type RM Length L Ch R = 1 ,17000   ,500,400,251
BEGIN DESCRIPTION:
SALUDA RIVER 37.0 XS N
END DESCRIPTION:
XS GIS Cut Line= 3
       1969399.2       798164.06      1969175.35       797137.59
      1969019.47       796487.82
#Sta/Elev= 30
 4011.22  212.12 4056.89  210.97 4082.83  207.92  4095.7  203.74 4124.55  194.36
 4204.99  188.58 4316.34  177.22 4339.36  176.31 4347.73  179.34 4359.28  180.29
 4411.72  173.48 4481.07  170.07 4499.11  171.67 4544.12  167.52  4717.4  165.94
 4843.51  168.78  4873.3  166.51 4918.59     164 4965.57  155.45 4998.46  154.95
 5079.65  163.95 5147.12  166.09 5170.99  165.51 5183.02  161.28 5207.92  166.14
 5292.49  169.05 5334.97  181.73 5368.61  193.66 5439.27  208.57 5626.37  211.22
#Mann= 5 ,-1,0
 4011.22     .06       0  4095.7     .15       0  4873.3    .045       0
 5147.12     .15       0 5334.97      .1       0
#XS Ineff= 2 , 0
     300 4528.62     212             300
Permanent Ineff=
       F       F
Bank Sta=4873.3,5147.12
XS Rating Curve= 0 ,0
Skew Angle= 20
Exp/Cntr=0.3,0.1

Type RM Length L Ch R = 1 ,16600   ,671,400,215
BEGIN DESCRIPTION:
SALUDA RIVER 36.0
END DESCRIPTION:
XS GIS Cut Line= 3
       1970093.6       797930.83      1969538.96       796992.96
      1969111.71       796517.66
#Sta/Elev= 30
  3910.4   202.2  3985.7   195.6  4107.9   189.5    4169  186.02    4217  187.29
  4311.5  185.43  4346.1  176.28  4365.7  175.02  4400.2  179.78  4418.2  177.65
  4435.2  170.63  4478.9  168.95  4494.5  171.18  4522.9  170.93  4541.7  168.54
  4593.5  167.41  4776.9  167.73  4796.2   165.8    4860     163    4965  155.28
    5000  154.78    5035  159.78  5194.6  164.89    5311  167.04  5336.9  170.72
  5391.8  191.62  5426.1  197.06  5482.1  204.81  5549.8   210.1  5639.1  207.76
#Mann= 6 ,-1,0
  3910.4     .12       0  4107.9     .06       0  4311.5     .15       0
  4796.2    .045       0  5194.6     .15       0  5426.1      .1       0
Bank Sta=4796.2,5194.6
XS Rating Curve= 0 ,0
Exp/Cntr=0.3,0.1

Type RM Length L Ch R = 1 ,16200   ,568,500,361
BEGIN DESCRIPTION:
SALUDA RIVER 35.0
END DESCRIPTION:
XS GIS Cut Line= 3
      1971090.43       797146.26      1969782.51       796678.06
      1969215.04       796524.44
#Sta/Elev= 30
  3610.8  197.35  3697.8  195.76  3803.7  190.58  4097.7  184.64    4114  182.99
  4148.6     188  4187.3  188.65  4201.4  182.75  4234.3  184.75  4321.5  183.92
  4335.8  176.91  4339.7  177.28  4390.9  179.24  4412.2  177.51  4431.1  172.82
    4475   171.8  4535.1  166.03  4553.5     168  4663.5  162.39    4820     161
    5000  153.94    5035  158.94  5196.4  164.44  5323.4  160.47  5331.9  163.23
  5370.1  164.58  5395.3  182.36  5436.7  200.68  5520.6  208.25  5587.9  209.35
#Mann= 6 ,-1,0
  3610.8     .12       0  4097.7     .06       0  4339.7     .15       0
  4663.5    .045       0  5196.4     .15       0  5520.6      .1       0
Bank Sta=4663.5,5196.4
XS Rating Curve= 0 ,0
Exp/Cntr=0.3,0.1

Type RM Length L Ch R = 1 ,15700   ,479,500,875
BEGIN DESCRIPTION:
SALUDA RIVER 34.0
END DESCRIPTION:
XS GIS Cut Line= 3
      1970790.53       796347.75      1969944.34       796211.38
      1969069.45       796253.32
#Sta/Elev= 30
  4142.9  182.14  4157.4  181.41  4167.8  178.59  4206.9  178.57    4219  180.23
  4254.3  179.77  4274.1  182.13  4411.1  170.99  4460.4  170.63  4480.9  167.88
    4521  166.97  4645.1  166.22  4714.1  161.92    4830     160    5000  152.72
    5035  157.72  5086.4  161.72  5160.6   161.3  5182.6  165.34  5270.9  164.05
  5280.6  162.18  5499.7  158.96  5510.6  162.45  5546.1  163.01  5634.8  164.34
  5656.4  167.27  5740.3  191.62  5773.3  192.82    5808  194.09  5875.9  201.84
#Mann= 6 ,-1,0
  4142.9     .15       0  4714.1    .045       0  5086.4     .15       0
  5270.9    .045       0  5546.1     .15       0  5773.3      .1       0
Bank Sta=4714.1,5086.4
XS Rating Curve= 0 ,0
Exp/Cntr=0.3,0.1

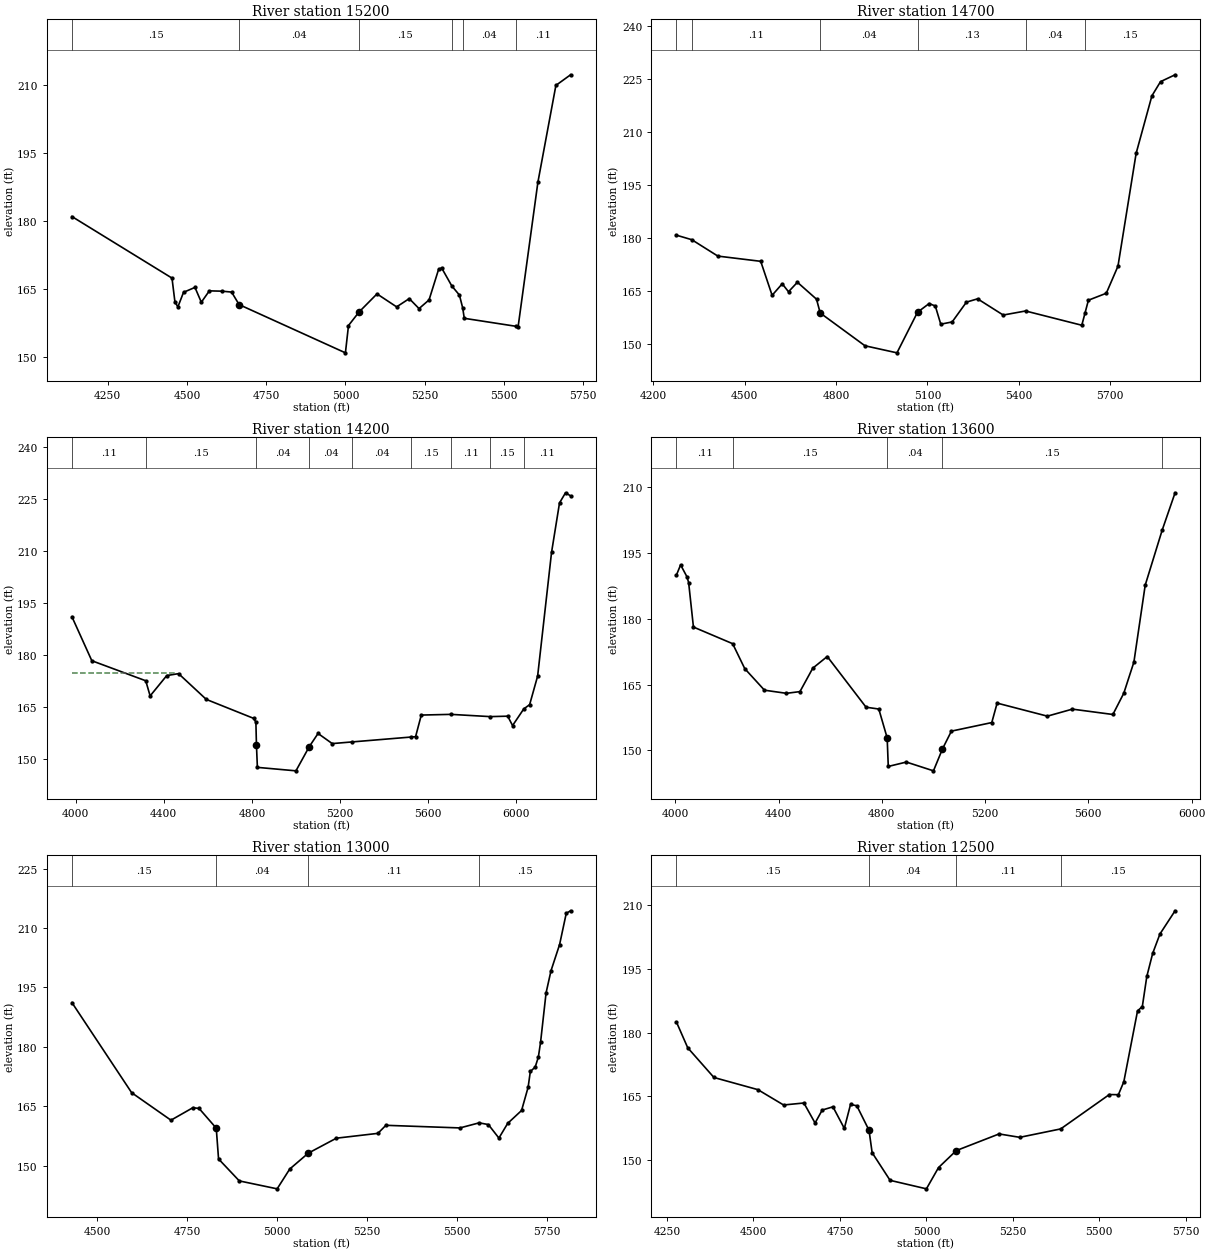
Type RM Length L Ch R = 1 ,15200   ,373,500,257
BEGIN DESCRIPTION:
SALUDA RIVER 33.0
END DESCRIPTION:
XS GIS Cut Line= 3
      1970772.22       795887.77      1969927.54        795712.4
      1969279.56       795421.69
#Sta/Elev= 30
  4137.3  180.98    4453  167.41  4462.3  162.13  4471.6  161.07  4489.4  164.28
  4525.4  165.36  4545.5  162.09  4570.8   164.6  4610.8  164.53    4641  164.33
  4664.7  161.57    5000  150.94  5009.7  156.96    5043  159.94  5099.6  163.93
  5161.5  161.07  5201.4  162.89  5232.2  160.69  5263.8   162.6  5293.8  169.31
  5303.6  169.64  5335.6  165.68  5359.6  163.67    5370  160.81  5374.9  158.55
    5537   156.8  5544.8  156.72  5607.1  188.53  5663.9  209.88  5710.2  212.22
#Mann= 6 ,-1,0
  4137.3     .15       0  4664.7     .04       0    5043     .15       0
  5335.6     .11       0    5370     .04       0    5537     .11       0
Bank Sta=4664.7,5043
XS Rating Curve= 0 ,0
Exp/Cntr=0.3,0.1

Type RM Length L Ch R = 1 ,14700   ,508,500,394
BEGIN DESCRIPTION:
SALUDA RIVER 32.0
END DESCRIPTION:
XS GIS Cut Line= 3
       1970827.1        795644.1      1970173.87       795332.59
      1969267.43       795226.75
#Sta/Elev= 30
  4276.3  180.81  4326.7  179.53  4412.2  174.89  4552.9  173.41  4590.3  163.79
  4623.5  167.05  4644.1  164.79  4673.3  167.48    4736  162.69  4748.1  158.78
    4895   149.5    5000   147.5  5067.4  158.99  5105.6  161.45  5125.8  160.76
  5143.7  155.61  5181.1  156.25    5228  161.86  5264.6  162.79  5348.6   158.2
    5422  159.35  5606.5  155.31  5616.8  158.68  5628.2   162.4  5686.9  164.37
  5725.2  172.04  5784.8  203.98  5836.5  220.25  5864.8  224.27  5912.6  226.22
#Mann= 6 ,-1,0
  4276.3     .15       0  4326.7     .11       0  4748.1     .04       0
  5067.4     .13       0    5422     .04       0  5616.8     .15       0
Bank Sta=4748.1,5067.4
XS Rating Curve= 0 ,0
Exp/Cntr=0.3,0.1

Type RM Length L Ch R = 1 ,14200   ,494,600,1335
BEGIN DESCRIPTION:
SALUDA RIVER 31.0
END DESCRIPTION:
XS GIS Cut Line= 3
      1971321.04       795296.85      1970388.47       794891.38
      1969142.49       794852.07
#Sta/Elev= 30
  3983.1  190.99  4073.5  178.29  4318.3  172.51  4338.1  168.14  4413.6  174.01
  4467.2  174.57    4593  167.14  4807.5  161.68  4818.2  160.61  4820.7  154.03
    4825  147.53    5000  146.53  5060.7  153.53  5100.4  157.31  5164.8  154.39
  5256.7  154.88  5522.6  156.28  5543.1  156.39    5569  162.62  5703.4  162.82
  5881.9  162.17  5961.3   162.3  5983.3  159.59    6034  164.38  6060.8  165.63
  6097.1  173.88  6160.2  209.53  6196.4  223.81  6223.7  226.74  6246.6  225.84
#Mann= 9 ,-1,0
  3983.1     .11       0  4318.3     .15       0  4820.7     .04       0
  5060.7     .04       0  5256.7     .04       0  5522.6     .15       0
  5703.4     .11       0  5881.9     .15       0    6034     .11       0
#XS Ineff= 2 , 0
       0    4450   174.7               0
Permanent Ineff=
       F       F
Bank Sta=4820.7,5060.7
XS Rating Curve= 0 ,0
Exp/Cntr=0.3,0.1

Type RM Length L Ch R = 1 ,13600   ,580,600,593
BEGIN DESCRIPTION:
SALUDA RIVER 30.0
END DESCRIPTION:
XS GIS Cut Line= 3
       1971368.8       795193.44      1970749.15       794414.17
      1970242.17       793627.48
#Sta/Elev= 30
  4004.4  189.92  4020.6  192.26  4045.2  189.54  4051.7  188.23  4070.3   178.1
  4222.2  174.31  4269.1  168.63  4345.5  163.72  4430.4  163.01  4482.9   163.4
  4532.5  168.73  4588.6  171.39  4738.9  159.85  4788.3  159.43  4820.7  152.86
    4825  146.36    4895  147.36    5000  145.36    5035  150.36  5069.5   154.4
  5225.9  156.35  5246.6  160.78  5441.2  157.81    5538  159.41    5695  158.19
  5737.3  163.04  5776.4  170.13  5820.2  187.64  5885.9  200.16  5935.9  208.67
#Mann= 5 ,-1,0
  4004.4     .11       0  4222.2     .15       0  4820.7     .04       0
    5035     .15       0  5885.9     .12       0
Bank Sta=4820.7,5035
XS Rating Curve= 0 ,0
Exp/Cntr=0.3,0.1

Type RM Length L Ch R = 1 ,13000   ,486,500,423
BEGIN DESCRIPTION:
SALUDA RIVER 29.0
END DESCRIPTION:
XS GIS Cut Line= 3
      1971558.15       794559.65      1971247.65       794082.11
      1970790.48       793408.14
#Sta/Elev= 30
  4430.4  191.19  4596.2  168.45  4705.3  161.51  4766.3  164.67  4783.4  164.47
    4831   159.5  4837.4  151.73    4895  146.19    5000  144.19    5035  149.19
  5086.4  153.19  5164.4  156.97  5279.7  158.19  5301.8  160.22  5507.4  159.56
  5560.6  160.84  5586.2  160.41  5615.5     157  5639.9  160.71  5678.4  163.96
  5696.6  169.83  5702.7   173.8  5716.1   174.9    5725  177.43  5731.2  181.24
  5746.4  193.64  5760.1  199.23  5783.9  205.82  5802.4  213.71  5814.4  214.35
#Mann= 4 ,-1,0
  4430.4     .15       0    4831     .04       0  5086.4     .11       0
  5560.6     .15       0
Bank Sta=4831,5086.4
XS Rating Curve= 0 ,0
Exp/Cntr=0.3,0.1

Type RM Length L Ch R = 1 ,12500   ,455,500,763
BEGIN DESCRIPTION:
SALUDA RIVER 28.0
END DESCRIPTION:
XS GIS Cut Line= 3
      1972005.95       794401.26      1971642.46       793776.63
      1971146.88       793255.84
#Sta/Elev= 30
  4277.3  182.48    4310  176.41  4385.8  169.42  4512.8  166.56  4587.1  162.95
  4645.8  163.42  4678.1  158.71  4698.8  161.76  4729.8  162.52  4762.7  157.44
  4780.6  163.07  4798.8  162.77  4834.1     157  4843.1  151.73    4895  145.22
    5000  143.22    5035  148.22  5086.4  152.22  5210.1  156.14  5269.9  155.34
  5388.2  157.32  5528.9  165.41    5555  165.37  5570.7  168.42  5610.4   185.1
  5624.2  186.11  5637.2  193.21  5654.1  198.62  5675.1  203.18  5718.9  208.65
#Mann= 4 ,-1,0
  4277.3     .15       0  4834.1     .04       0  5086.4     .11       0
  5388.2     .15       0
Bank Sta=4834.1,5086.4
XS Rating Curve= 0 ,0
Exp/Cntr=0.3,0.1

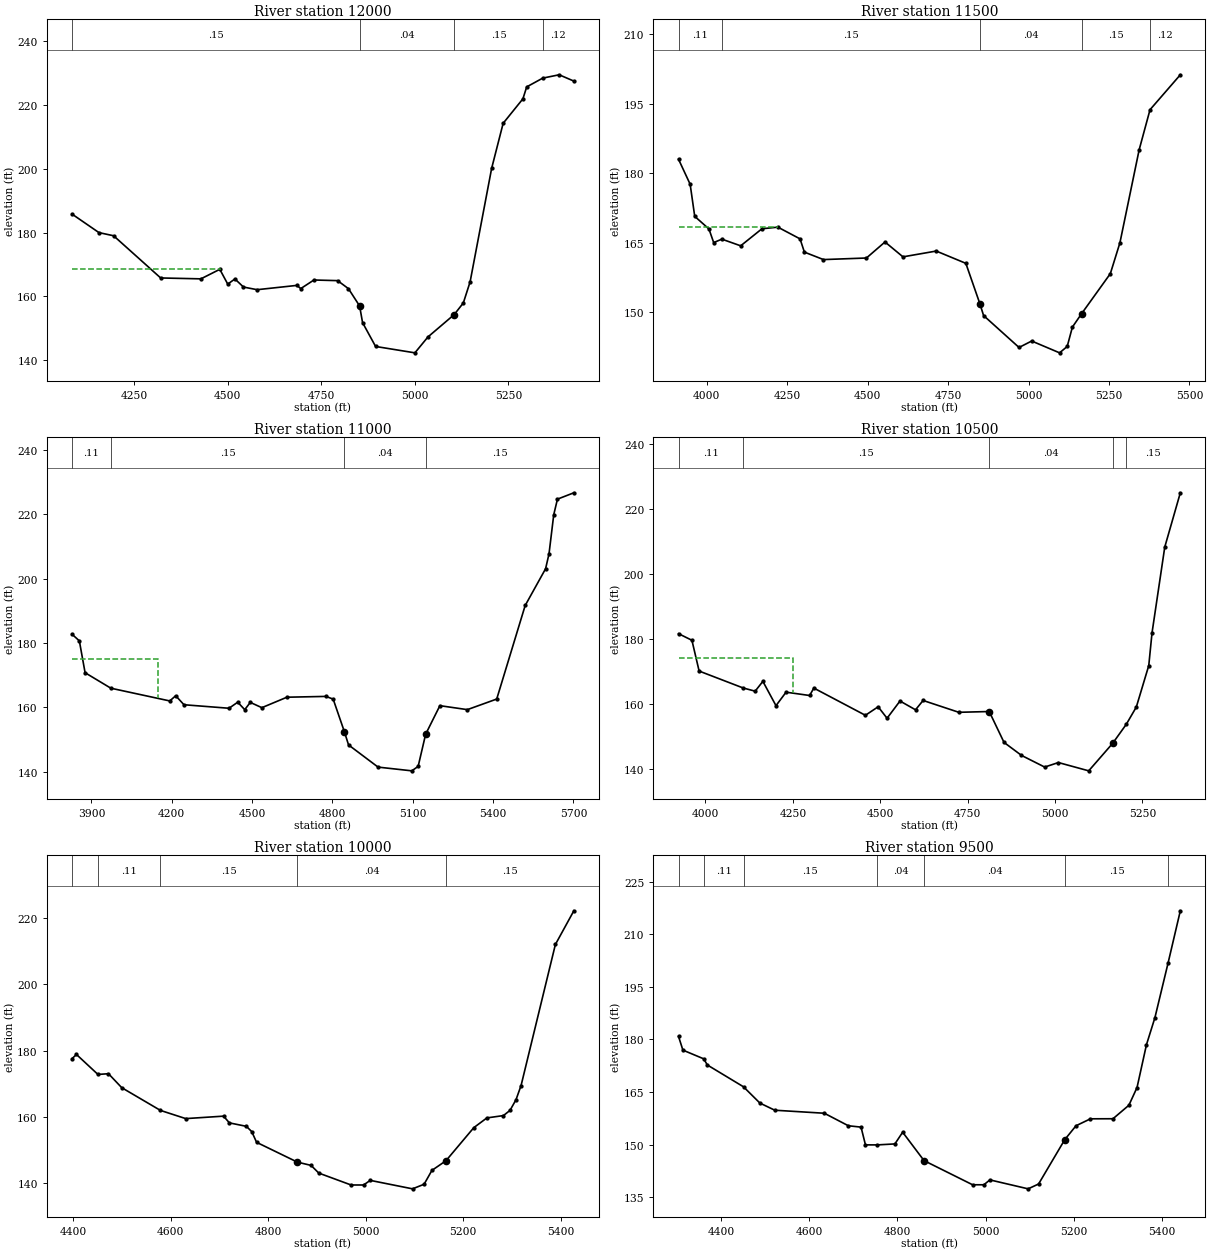
Type RM Length L Ch R = 1 ,12000   ,505,500,406
BEGIN DESCRIPTION:
SALUDA RIVER 27.0
END DESCRIPTION:
XS GIS Cut Line= 3
      1972386.71       794416.48      1972085.09       793551.67
      1971917.58        793161.4
#Sta/Elev= 30
  4084.1  185.77  4155.9  179.97    4195  178.98  4320.8  165.74  4428.3  165.46
  4478.8  168.45    4500  163.81  4519.2  165.43    4542  162.89  4578.5  162.06
  4684.8  163.41  4695.1  162.41  4730.3   165.1  4793.6   164.9  4822.5  162.38
  4852.3  156.96  4860.2  151.73    4895  144.25    5000  142.25    5035  147.25
    5105  154.25  5129.4   157.9  5147.5  164.52    5205   200.1  5235.8  214.26
  5288.6  221.94  5298.7  225.68  5341.5  228.43  5385.4  229.48  5424.7   227.5
#Mann= 4 ,-1,0
  4084.1     .15       0  4852.3     .04       0    5105     .15       0
  5341.5     .12       0
#XS Ineff= 2 , 0
       0    4480   168.7               0
Permanent Ineff=
       F       F
Bank Sta=4852.3,5105
XS Rating Curve= 0 ,0
Exp/Cntr=0.3,0.1

Type RM Length L Ch R = 1 ,11500   ,384,500,897
BEGIN DESCRIPTION:
SALUDA RIVER 26.0
END DESCRIPTION:
XS GIS Cut Line= 3
      1972936.22       794374.07      1972543.94       793359.57
       1972176.5       793063.94
#Sta/Elev= 30
  3912.3  183.05  3948.4  177.66  3962.6  170.73  4006.8  168.01  4021.5  165.07
    4047  165.81  4105.4  164.37  4171.5  168.05    4221   168.4  4289.9  165.87
  4303.4  163.01  4362.7   161.4  4496.2  161.74  4553.9   165.2  4609.7  161.99
  4713.1  163.24  4805.1  160.59  4849.4  151.73  4860.2  149.32  4970.4  142.43
  5009.7  143.82  5096.4  141.27  5120.1  142.65  5136.2  146.83    5165  149.74
  5254.1  158.36  5283.9  165.03  5343.6  185.08  5377.4  193.75  5471.6  201.29
#Mann= 5 ,-1,0
  3912.3     .11       0    4047     .15       0  4849.4     .04       0
    5165     .15       0  5377.4     .12       0
#XS Ineff= 2 , 0
       0    4220  168.42               0
Permanent Ineff=
       F       F
Bank Sta=4849.4,5165
XS Rating Curve= 0 ,0
Exp/Cntr=0.3,0.1

Type RM Length L Ch R = 1 ,11000   ,398,500,523
BEGIN DESCRIPTION:
SALUDA RIVER 25.0
END DESCRIPTION:
XS GIS Cut Line= 3
       1972975.8       794356.93      1973004.91       793184.99
      1973233.56       792521.69
#Sta/Elev= 30
  3827.7  182.72  3854.9  180.67  3876.3  170.78  3972.5  165.97  4192.6  162.01
  4214.7  163.63  4245.6  160.83  4413.8  159.74  4446.3  161.62  4472.5   159.3
  4493.2  161.56  4536.5  159.92    4630  163.17    4776  163.42  4802.8  162.57
  4844.6  152.46  4860.2  148.35  4970.4  141.46  5096.4   140.3  5120.1  141.68
  5148.1  151.67  5201.3  160.54  5303.9  159.31  5413.5   162.6  5519.8  191.66
    5596  203.07  5608.8  207.69  5626.5  219.87  5640.3  224.69  5701.6  226.67
#Mann= 4 ,-1,0
  3827.7     .11       0  3972.5     .15       0  4844.6     .04       0
  5148.1     .15       0
#XS Ineff= 2 , 0
       0    4150     175               0
Permanent Ineff=
       F       F
Bank Sta=4844.6,5148.1
XS Rating Curve= 0 ,0
Exp/Cntr=0.3,0.1

Type RM Length L Ch R = 1 ,10500   ,779,500,198
BEGIN DESCRIPTION:
SALUDA RIVER 24.0
END DESCRIPTION:
XS GIS Cut Line= 3
       1973092.9       794313.93      1973478.94       793308.39
      1973639.32       792987.76
#Sta/Elev= 30
  3922.9  181.53  3961.2   179.5  3981.8  170.03  4107.9  164.82  4142.1  163.84
  4164.2  166.86  4201.7  159.38  4230.5  163.53  4297.9  162.51    4310  164.79
  4457.5  156.42    4494  159.04  4519.5  155.51  4556.5  160.81  4600.9  158.11
  4622.6  160.98  4724.8  157.34  4811.8  157.58  4854.1  148.08  4904.1  144.08
  4970.4  140.49  5009.7  141.88  5096.4  139.33    5165   147.8  5203.9  153.65
  5232.6  158.96  5268.2  171.72  5277.5  181.76    5314  208.19  5358.5  224.88
#Mann= 5 ,-1,0
  3922.9     .11       0  4107.9     .15       0  4811.8     .04       0
    5165     .15       0  5203.9     .15       0
#XS Ineff= 2 , 0
       0    4250     174               0
Permanent Ineff=
       F       F
Bank Sta=4811.8,5165
XS Rating Curve= 0 ,0
Exp/Cntr=0.3,0.1

Type RM Length L Ch R = 1 ,10000   ,530,500,501
BEGIN DESCRIPTION:
SALUDA RIVER 23.0
END DESCRIPTION:
XS GIS Cut Line= 3
      1974218.09       793859.03      1973948.16       793320.82
      1973672.84       792993.92
#Sta/Elev= 30
  4397.9  177.61  4406.9  178.86    4451  172.84  4472.6  173.06  4499.8  168.85
  4579.2     162  4631.1  159.53  4708.7  160.27  4720.7  158.24  4755.5   157.2
  4766.5  155.61  4776.5  152.38  4860.2  146.41  4888.2  145.43  4904.1  143.11
  4970.4  139.52  4995.9  139.52  5009.7  140.91  5096.4  138.36  5120.1  139.74
  5136.2  143.92    5165  146.83  5222.1   156.8    5249  159.74  5282.9  160.44
  5296.4  162.01  5308.7  165.22  5319.1   169.5  5389.5  212.01  5427.4  222.17
#Mann= 5 ,-1,0
  4397.9     .06       0    4451     .11       0  4579.2     .15       0
  4860.2     .04       0    5165     .15       0
Bank Sta=4860.2,5165
XS Rating Curve= 0 ,0
Exp/Cntr=0.3,0.1

Type RM Length L Ch R = 1 ,9500    ,484,500,500
BEGIN DESCRIPTION:
SALUDA RIVER 22.0
END DESCRIPTION:
XS GIS Cut Line= 3
      1974714.62       793590.97       1974335.5       793006.34
      1974044.47       792674.07
#Sta/Elev= 30
  4303.2  180.84  4313.1  176.94  4360.3  174.46  4368.6   172.7  4450.6  166.48
  4487.8  161.84  4521.6   159.8    4634  158.94  4688.5  155.37  4717.3  154.98
  4727.3  149.92  4754.1  149.91  4794.1  150.19  4811.7  153.53  4860.2  145.43
  4970.4  138.54  4995.9  138.54  5009.7  139.93  5096.4  137.38  5120.1  138.76
  5179.5  151.41    5205  155.37  5237.8  157.35  5288.9  157.37    5325  161.22
  5343.5  166.28  5364.9   178.5  5384.1  186.22    5414  201.83  5441.7  216.68
#Mann= 7 ,-1,0
  4303.2     .06       0  4360.3     .11       0  4450.6     .15       0
  4754.1     .04       0  4860.2     .04       0  5179.5     .15       0
    5414     .12       0
Bank Sta=4860.2,5179.5
XS Rating Curve= 0 ,0
Exp/Cntr=0.3,0.1

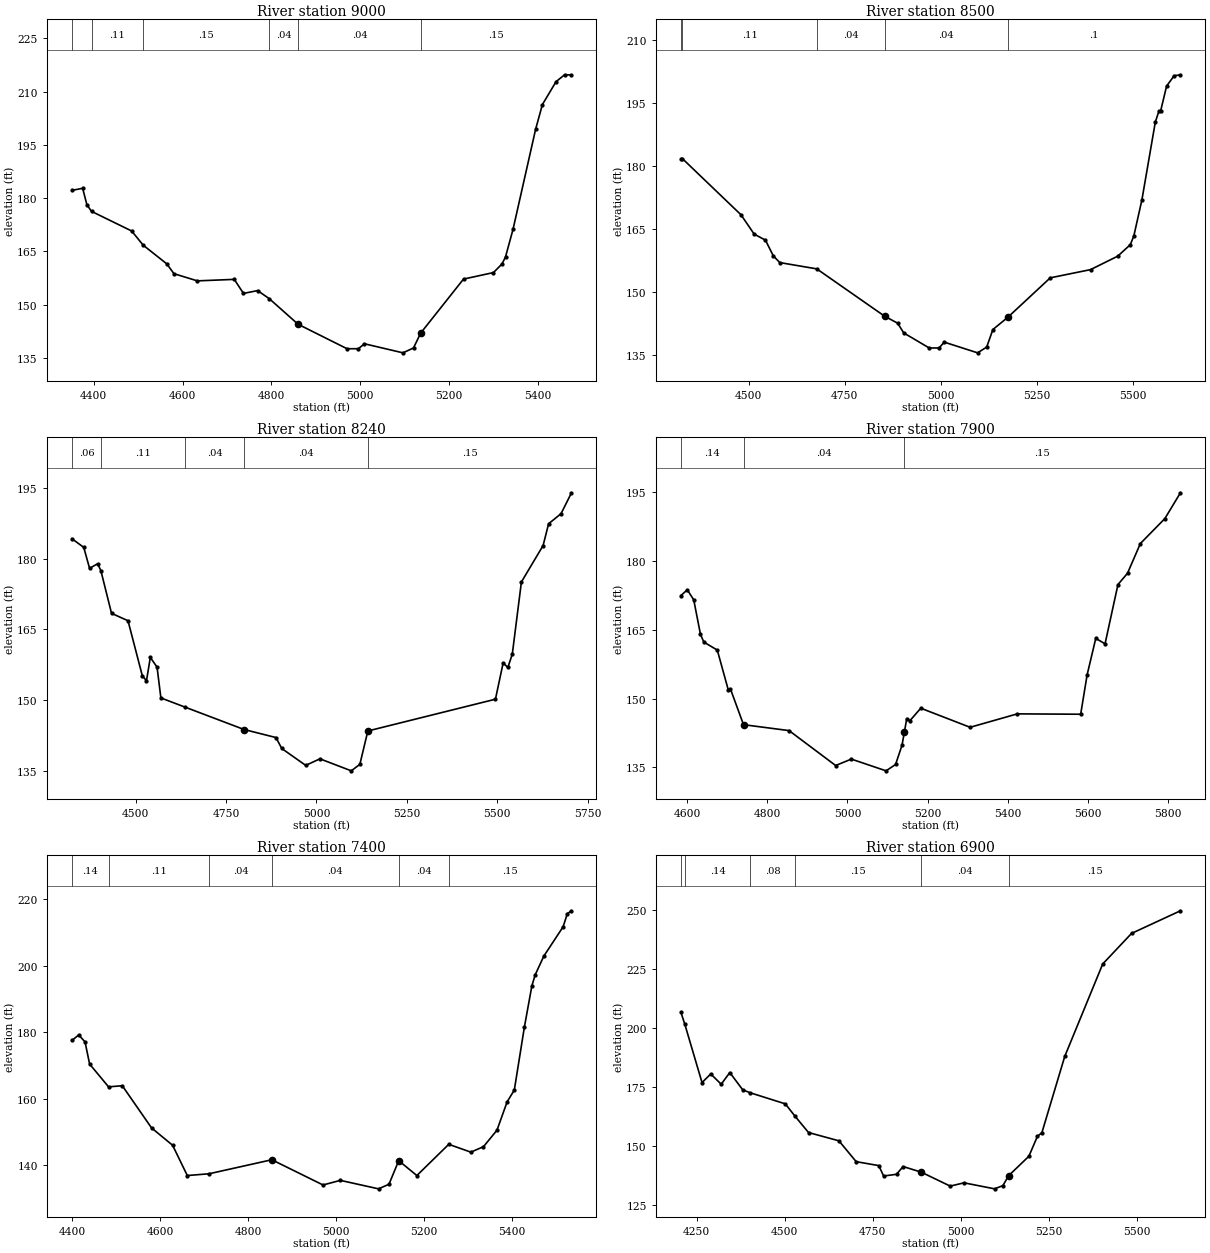
Type RM Length L Ch R = 1 ,9000    ,299,500,620
BEGIN DESCRIPTION:
SALUDA RIVER 21.0
END DESCRIPTION:
XS GIS Cut Line= 3
       1975095.4       793322.92      1974770.61       792760.92
      1974467.84       792393.76
#Sta/Elev= 30
  4350.9  182.19    4375  182.77  4384.6  178.12    4395  176.27  4485.4  170.74
  4511.3  166.75  4564.5  161.48  4580.6  158.71  4633.3  156.69  4716.4  157.11
  4737.2  153.15    4769  153.95  4795.2  151.68  4860.2  144.46  4970.4  137.57
  4995.9  137.57  5009.7  138.96  5096.4  136.41  5120.1  137.79  5136.2  141.97
  5232.7  157.19  5300.2  159.03  5319.4  161.45  5327.3  163.44  5344.2   171.2
  5395.1  199.41  5410.4  206.37  5441.1  212.82  5460.3  214.76  5475.9  214.71
#Mann= 6 ,-1,0
  4350.9     .06       0    4395     .11       0  4511.3     .15       0
  4795.2     .04       0  4860.2     .04       0  5136.2     .15       0
Bank Sta=4860.2,5136.2
XS Rating Curve= 0 ,0
Exp/Cntr=0.3,0.1

Type RM Length L Ch R = 1 ,8500    ,278,260,299
BEGIN DESCRIPTION:
SALUDA RIVER 20.0
END DESCRIPTION:
XS GIS Cut Line= 3
      1975275.11       793277.21      1975238.69       792601.99
      1975058.82       792003.85
#Sta/Elev= 30
  4323.8  181.73  4327.9  181.75  4480.3  168.37  4514.6  163.76    4544  162.32
  4564.5  158.56  4581.4  156.97  4677.6  155.47  4854.1  144.19  4888.2  142.51
  4904.1  140.19  4970.4   136.6  4995.9   136.6  5009.7  137.99  5096.4  135.44
  5120.1  136.82  5136.2     141    5175  143.91  5285.6  153.33  5390.5  155.29
  5461.3   158.5  5494.2  161.25  5503.3  163.35  5524.2   171.9  5559.2   190.5
  5568.4  193.04  5572.9  193.09  5588.6  199.08  5608.1  201.53  5624.6  201.77
#Mann= 5 ,-1,0
  4323.8     .06       0  4327.9     .11       0  4677.6     .04       0
  4854.1     .04       0    5175      .1       0
Bank Sta=4854.1,5175
XS Rating Curve= 0 ,0
Exp/Cntr=0.3,0.1

Type RM Length L Ch R = 1 ,8240    ,506,340,167
BEGIN DESCRIPTION:
SALUDA RIVER 19.0
END DESCRIPTION:
XS GIS Cut Line= 4
      1975561.45       793249.76      1975497.34        792576.8
      1975363.45       792162.28      1975183.71       791961.22
#Sta/Elev= 30
    4324  184.24  4356.6  182.41  4372.7  177.96    4395  178.93  4403.9  177.49
  4433.4   168.4    4479  166.82  4518.7  155.09  4530.1  154.08  4540.7  159.03
  4559.3  156.96  4569.9  150.42  4637.3  148.45    4800  143.71  4888.2     142
  4904.1  139.68  4970.4  136.09  5009.7  137.48  5096.4  134.93  5120.1  136.31
  5142.2   143.4    5495  150.15  5516.3  157.86  5529.4  156.89  5541.6  159.72
  5566.8  175.06  5626.8   182.8    5642  187.43  5676.4  189.57  5705.3  194.01
#Mann= 5 ,-1,0
    4324     .06       0  4403.9     .11       0  4637.3     .04       0
    4800     .04       0  5142.2     .15       0
Bank Sta=4800,5142.2
XS Rating Curve= 0 ,0
Exp/Cntr=0.3,0.1

Type RM Length L Ch R = 1 ,7900    ,486,500,550
BEGIN DESCRIPTION:
SALUDA RIVER 18.0
END DESCRIPTION:
XS GIS Cut Line= 3
      1976019.28       792850.52       1975821.7       792484.31
      1975193.71       791939.01
#Sta/Elev= 30
  4583.9  172.39  4599.9  173.64    4616  171.45  4632.8  163.95  4641.1  162.28
  4674.8  160.53  4702.2  151.89  4707.5  152.11  4740.3  144.31  4854.1  143.02
  4970.4  135.43  5009.7  136.82  5096.4  134.27  5120.1  135.65  5136.2  139.83
  5142.2  142.74  5148.1  145.64  5155.7  145.15  5183.1  147.89  5306.3  143.74
  5424.3  146.66  5582.5  146.58  5598.6  155.14  5620.2  163.08  5643.4  161.89
  5675.6  174.78  5699.5  177.24  5731.6   183.7  5792.8  189.13  5831.7  194.74
#Mann= 3 ,-1,0
  4583.9     .14       0  4740.3     .04       0  5142.2     .15       0
Bank Sta=4740.3,5142.2
XS Rating Curve= 0 ,0
Exp/Cntr=0.3,0.1

Type RM Length L Ch R = 1 ,7400    ,509,500,521
BEGIN DESCRIPTION:
SALUDA RIVER 17.0
END DESCRIPTION:
XS GIS Cut Line= 3
      1976384.47       792537.43      1976039.57       792046.83
      1975698.52       791635.28
#Sta/Elev= 30
  4400.3  177.51  4415.6  179.17    4430  177.07  4440.4  170.41  4483.4  163.55
  4514.6  163.89    4581   151.2  4628.8  145.98  4662.2  136.87  4711.4   137.4
  4854.1  141.62  4970.4  134.03  5009.7  135.42  5096.4  132.87  5120.1  134.25
  5142.2  141.34  5183.4  136.87  5255.8  146.26    5306  143.91  5334.7  145.56
  5365.3  150.51  5388.3  159.03  5404.7   162.6  5427.4  181.42  5444.6  193.98
  5452.2  197.29  5471.8  202.91  5515.4  211.69    5525  215.63  5534.5  216.52
#Mann= 6 ,-1,0
  4400.3     .14       0  4483.4     .11       0  4711.4     .04       0
  4854.1     .04       0  5142.2     .04       0  5255.8     .15       0
Bank Sta=4854.1,5142.2
XS Rating Curve= 0 ,0
Exp/Cntr=0.3,0.1

Type RM Length L Ch R = 1 ,6900    ,479,450,378
BEGIN DESCRIPTION:
SALUDA RIVER 16.0
END DESCRIPTION:
XS GIS Cut Line= 3
      1976827.42       792382.79      1976404.69       791709.85
      1976023.24       791215.51
#Sta/Elev= 30
  4205.3  206.79  4216.6   201.6  4265.3  176.95  4290.1   180.6  4319.8  176.24
  4344.2   181.2    4381  173.86  4402.2  172.62  4501.9  167.92  4529.7  162.65
  4567.8  155.76  4654.2  152.24  4703.2   143.4  4767.4  141.73  4781.2  137.31
  4817.8  138.04  4836.6  141.33  4888.2  138.94  4970.4  133.03  5009.7  134.42
  5096.4  131.87  5120.1  133.25  5136.2  137.43  5193.9  145.69    5218  154.11
  5230.9  155.74  5295.8  188.07  5403.6  227.25  5485.5  240.22  5624.4  249.82
#Mann= 6 ,-1,0
  4205.3     .06       0  4216.6     .14       0  4402.2     .08       0
  4529.7     .15       0  4888.2     .04       0  5136.2     .15       0
Bank Sta=4888.2,5136.2
XS Rating Curve= 0 ,0
Exp/Cntr=0.5,0.3

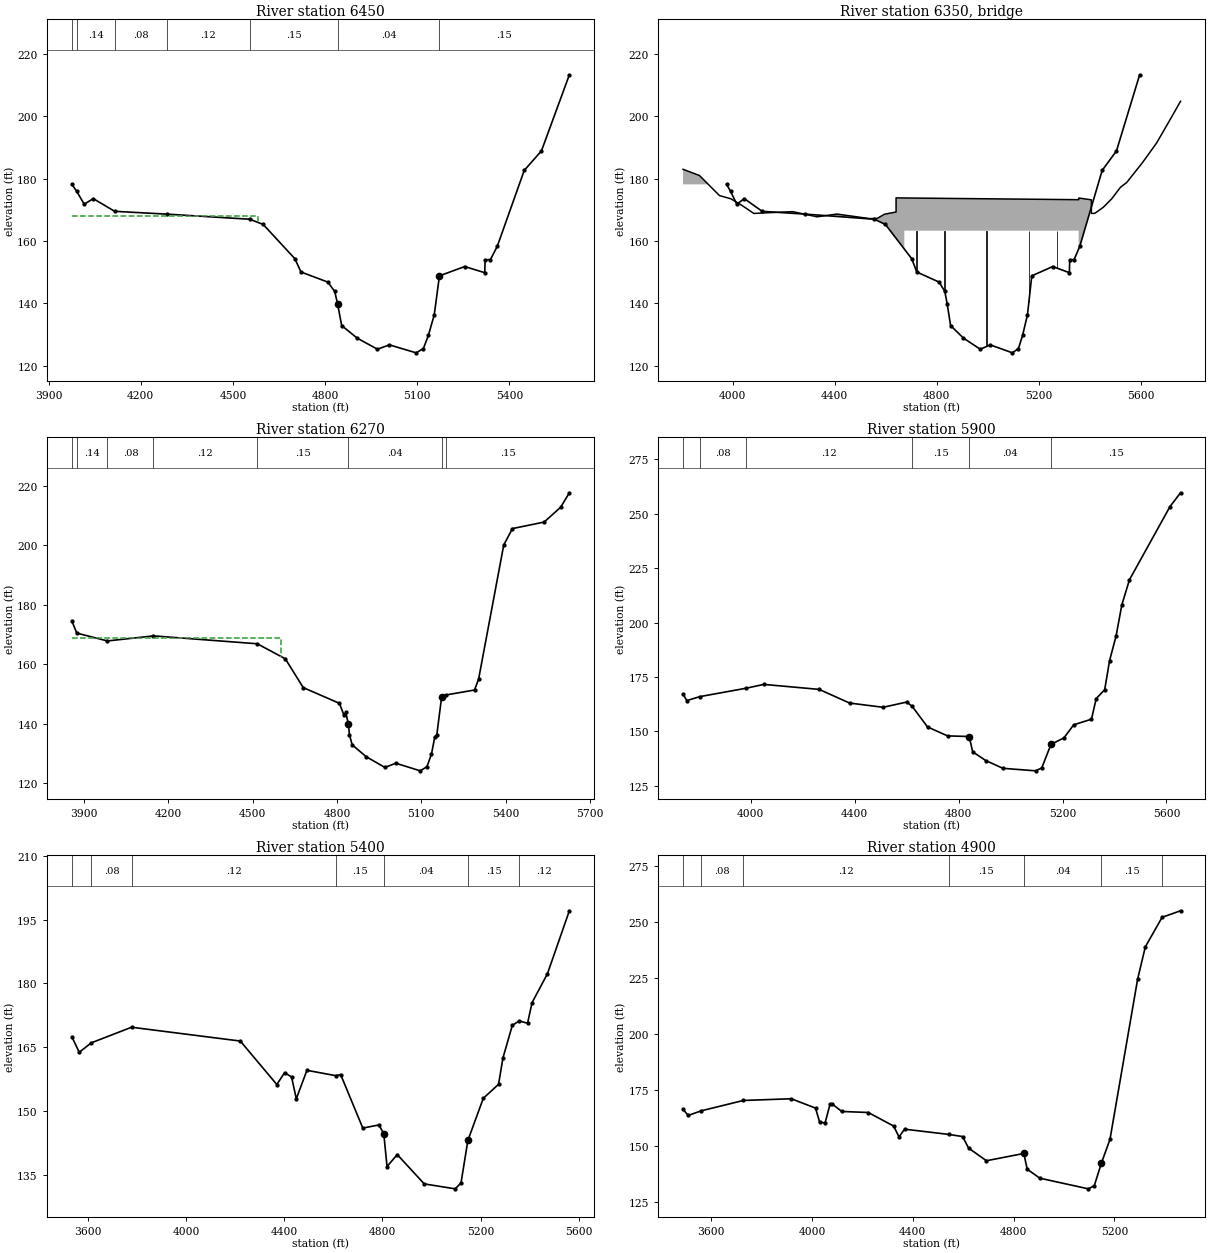
Type RM Length L Ch R = 1 ,6450    ,187,180,256
BEGIN DESCRIPTION:
SALUDA RIVER (Riverbanks Zoo - US)
END DESCRIPTION:
XS GIS Cut Line= 4
       1977292.9       792276.08      1977257.81       792069.43
      1976755.63       791428.17      1976269.39       791084.91
#Sta/Elev= 30
  3975.9  178.14  3991.4  175.95  4016.1  171.78  4045.5  173.57  4115.4   169.5
  4285.1   168.6  4554.6  166.97  4598.7  165.29  4701.8  154.32  4721.6  150.06
    4809  146.83  4831.4  143.85  4840.6  139.93  4854.1  132.91  4904.1  128.91
  4970.4  125.32  5009.7  126.71  5096.4  124.16  5120.1  125.54  5136.2  129.72
  5155.4  136.31  5172.3  148.82  5254.4  151.81  5319.8  149.84    5321  153.93
  5338.4  154.06  5360.7  158.32  5448.3  182.61  5504.4  188.87  5595.2  213.25
#Mann= 7 ,-1,0
  3975.9     .06       0  3991.4     .14       0  4115.4     .08       0
  4285.1     .12       0  4554.6     .15       0  4840.6     .04       0
  5172.3     .15       0
#XS Ineff= 2 , 0
       0  4582.8     168  5446.1       0  170.41
Permanent Ineff=
       F       F
Bank Sta=4840.6,5172.3
XS Rating Curve= 0 ,0
Exp/Cntr=0.5,0.3

Type RM Length L Ch R = 3 ,6350    ,,,
BEGIN DESCRIPTION:
SALUDA RIVER (Riverbanks Zoo - TOR)
Structure ID: R_SAL_01
Detailed Survey Structure
END DESCRIPTION:
Bridge Culvert--1,0,-1,-1, 0
Deck Dist Width WeirC Skew NumUp NumDn MinLoCord MaxHiCord MaxSubmerge Is_Ogee
90,20,3,0, 32, 32, , , 0.95, 0, 1,1,,
  3805.3  3869.8  3948.1  3993.4  4035.5  4082.9  4140.5  4234.9    4331  4408.5
  4536.4  4566.6  4595.3  4640.4  4640.4  4672.8  4672.8  5356.1  5356.1  5356.6
  5356.7    5406    5406  5419.5  5452.6  5485.5  5520.1  5544.2  5606.1  5662.2
  5720.9  5755.5
  182.97  180.97  174.55   173.5  171.43  168.82  169.06   169.4  167.74  168.63
  167.17  167.24  168.58  169.28  173.81  173.78  173.78  173.23  173.23  173.23
  173.77  173.18  168.82  168.86  170.79  173.49  177.22  178.71  185.09  191.46
  199.78  204.77
  104.16  104.16  104.16  104.16  104.16  104.16  104.16  104.16  104.16  104.16
  104.16  104.16  104.16  104.16  104.16  104.16   163.3   163.3  104.16  104.16
  104.16  104.16  104.16  104.16  104.16  104.16  104.16  104.16  104.16  104.16
  104.16  104.16
  3805.3  3869.8  3948.1  3993.4  4035.5  4082.9  4140.5  4234.9    4331  4408.5
  4536.4  4566.6  4595.3  4640.4  4640.4  4672.8  4672.8  5356.1  5356.1  5356.6
  5356.7    5406    5406  5419.5  5452.6  5485.5  5520.1  5544.2  5606.1  5662.2
  5720.9  5755.5
  182.97  180.97  174.55   173.5  171.43  168.82  169.06   169.4  167.74  168.63
  167.17  167.24  168.58  169.28  173.81  173.78  173.78  173.23  173.23  173.23
  173.77  173.18  168.82  168.86  170.79  173.49  177.22  178.71  185.09  191.46
  199.78  204.77
  104.16  104.16  104.16  104.16  104.16  104.16  104.16  104.16  104.16  104.16
  104.16  104.16  104.16  104.16  104.16  104.16   163.3   163.3  104.16  104.16
  104.16  104.16  104.16  104.16  104.16  104.16  104.16  104.16  104.16  104.16
  104.16  104.16
Pier Skew, UpSta & Num, DnSta & Num=  ,4721.6, 2 ,4721.6, 2 , 0 , 0 , 0 ,0,0
     2.5     2.5
  150.06   163.3
     2.5     2.5
  150.12   163.3
Pier Skew, UpSta & Num, DnSta & Num=  ,4831.4, 2 ,4831.4, 2 , 0 , 0 , 0 ,0,0
     2.5     2.5
  143.85   163.3
     2.5     2.5
  143.91   163.3
Pier Skew, UpSta & Num, DnSta & Num=  ,4995.9, 2 ,4995.9, 2 , 0 , 0 , 0 ,0,0
     2.5     2.5
  125.32   163.3
     2.5     2.5
  125.38   163.3
Pier Skew, UpSta & Num, DnSta & Num=  ,5161.1, 2 ,5161.1, 2 , 0 , 0 , 0 ,0,0
     2.5     2.5
  141.36   163.3
     2.5     2.5
  141.42   163.3
Pier Skew, UpSta & Num, DnSta & Num=  ,5271.2, 2 ,5271.2, 2 , 0 , 0 , 0 ,0,0
     2.5     2.5
  150.47   163.3
     2.5     2.5
  150.53   163.3
BR Coef= 1 , 1 , 0 ,1.25, 0 ,,,0.8,0,2,0,
WSPro=,,,, 1 ,,,, 0 ,,,, 0 ,,,,-1 ,-1 ,-1 , 0 , 0 , 0 , 0 , 0
BC Design=,, 0 ,, 0 ,,,,,,
BC HTab HWMax=213.25
BC Use User HTab Curves=0
BC User HTab FreeFlow(D)= 0

Type RM Length L Ch R = 1 ,6270    ,350,370,353
BEGIN DESCRIPTION:
SALUDA RIVER (Riverbanks Zoo - DS)
END DESCRIPTION:
XS GIS Cut Line= 4
        1977521.       792252.67      1977456.67       792007.05
      1976896.71       791316.44      1976509.18       790823.66
#Sta/Elev= 30
    3857  174.55  3874.6  170.48  3983.8  167.85  4147.4  169.55  4516.7   166.9
  4616.2  161.87  4680.2  152.18    4809  146.89  4825.1  142.92  4831.4  143.91
  4840.6  139.99  4844.6  136.38  4854.1  132.97  4904.1  128.97  4970.4  125.38
  5009.7  126.77  5096.4  124.22  5120.1   125.6  5136.2  129.78  5148.1  135.59
  5155.4  136.37  5172.3  148.88  5186.6  149.68  5289.5  151.37    5304  155.01
  5393.5   200.1  5424.6   205.6  5537.1  207.78  5596.3   212.8  5626.9  217.62
#Mann= 8 ,-1,0
    3857     .07       0  3874.6     .14       0  3983.8     .08       0
  4147.4     .12       0  4516.7     .15       0  4840.6     .04       0
  5172.3     .04       0  5186.6     .15       0
#XS Ineff= 2 , 0
       0  4602.8   168.7  5426.1       0  169.24
Permanent Ineff=
       F       F
Bank Sta=4840.6,5172.3
XS Rating Curve= 0 ,0
Exp/Cntr=0.5,0.3

Type RM Length L Ch R = 1 ,5900    ,475,500,577
BEGIN DESCRIPTION:
SALUDA RIVER 12.0
END DESCRIPTION:
XS GIS Cut Line= 3
      1977851.52       792172.26       1977193.9       791096.43
       1976744.6       790620.92
#Sta/Elev= 30
  3739.1  167.13  3753.6  164.17    3804  165.99  3980.4  169.81  4050.2   171.6
    4263  169.31  4380.2  163.03  4509.3  161.08  4600.1  163.49  4621.1  161.53
  4680.3  152.05  4757.2  147.94  4840.6  147.64  4854.1  140.62  4904.1  136.62
  4970.4  133.03  5096.4  131.87  5120.1  133.25  5155.4  144.02  5205.4  147.03
  5242.8  153.02  5311.3   155.6  5329.6  165.11  5362.2  169.15    5381  182.53
  5406.1  193.88  5428.1  208.09  5457.6  219.72  5613.8  253.38  5654.2  259.69
#Mann= 6 ,-1,0
  3739.1     .14       0    3804     .08       0  3980.4     .12       0
  4621.1     .15       0  4840.6     .04       0  5155.4     .15       0
Bank Sta=4840.6,5155.4
XS Rating Curve= 0 ,0
Exp/Cntr=0.3,0.1

Type RM Length L Ch R = 1 ,5400    ,412,500,635
BEGIN DESCRIPTION:
SALUDA RIVER 11.0
END DESCRIPTION:
XS GIS Cut Line= 4
      1977950.89       792189.73      1977743.74       791163.13
      1977578.28       790778.61       1977338.6       790270.61
#Sta/Elev= 30
  3534.1  167.46  3564.2   163.8  3613.2  166.02  3777.4  169.69  4220.7  166.44
  4369.4  156.23  4401.3  159.02  4429.6     158  4448.8  152.87  4492.2  159.57
  4610.2   158.3  4629.6  158.57  4719.8  145.99  4785.9  146.73  4805.5   144.6
  4818.6  136.96  4860.2  139.76  4970.4  132.87  5096.4  131.71  5120.1  133.09
  5148.1  143.08  5210.9  152.98  5273.2  156.28  5290.9  162.45  5329.2  170.13
  5357.2  171.17  5391.3  170.63  5409.7  175.48  5472.2  182.24  5561.7  197.06
#Mann= 7 ,-1,0
  3534.1     .14       0  3613.2     .08       0  3777.4     .12       0
  4610.2     .15       0  4805.5     .04       0  5148.1     .15       0
  5357.2     .12       0
Bank Sta=4805.5,5148.1
XS Rating Curve= 0 ,0
Exp/Cntr=0.3,0.1

Type RM Length L Ch R = 1 ,4900    ,419,500,637
BEGIN DESCRIPTION:
SALUDA RIVER 10.0
END DESCRIPTION:
XS GIS Cut Line= 3
       1978001.9        792181.5      1978051.23        790671.1
      1978078.83       790209.63
#Sta/Elev= 30
  3488.8  166.33  3509.4  163.63  3560.9  165.69  3728.3  170.31  3918.4  171.07
  4014.3   166.9    4031  160.55  4052.4  160.33  4072.2  168.72  4080.1  168.77
  4118.5   165.4  4223.6  164.94  4324.2   158.9  4345.6  154.04  4367.5  157.51
  4542.2  155.18  4597.8  154.21  4621.5  149.07  4692.3  143.43  4840.6  146.67
  4854.1  139.65  4904.1  135.65  5096.4   130.9  5120.1  132.28  5148.1  142.27
  5182.4  152.96  5292.1  224.43  5322.6   238.8  5389.2  251.98  5462.3  254.89
#Mann= 7 ,-1,0
  3488.8     .14       0  3560.9     .08       0  3728.3     .12       0
  4542.2     .15       0  4840.6     .04       0  5148.1     .15       0
  5389.2     .12       0
Bank Sta=4840.6,5148.1
XS Rating Curve= 0 ,0
Exp/Cntr=0.3,0.1