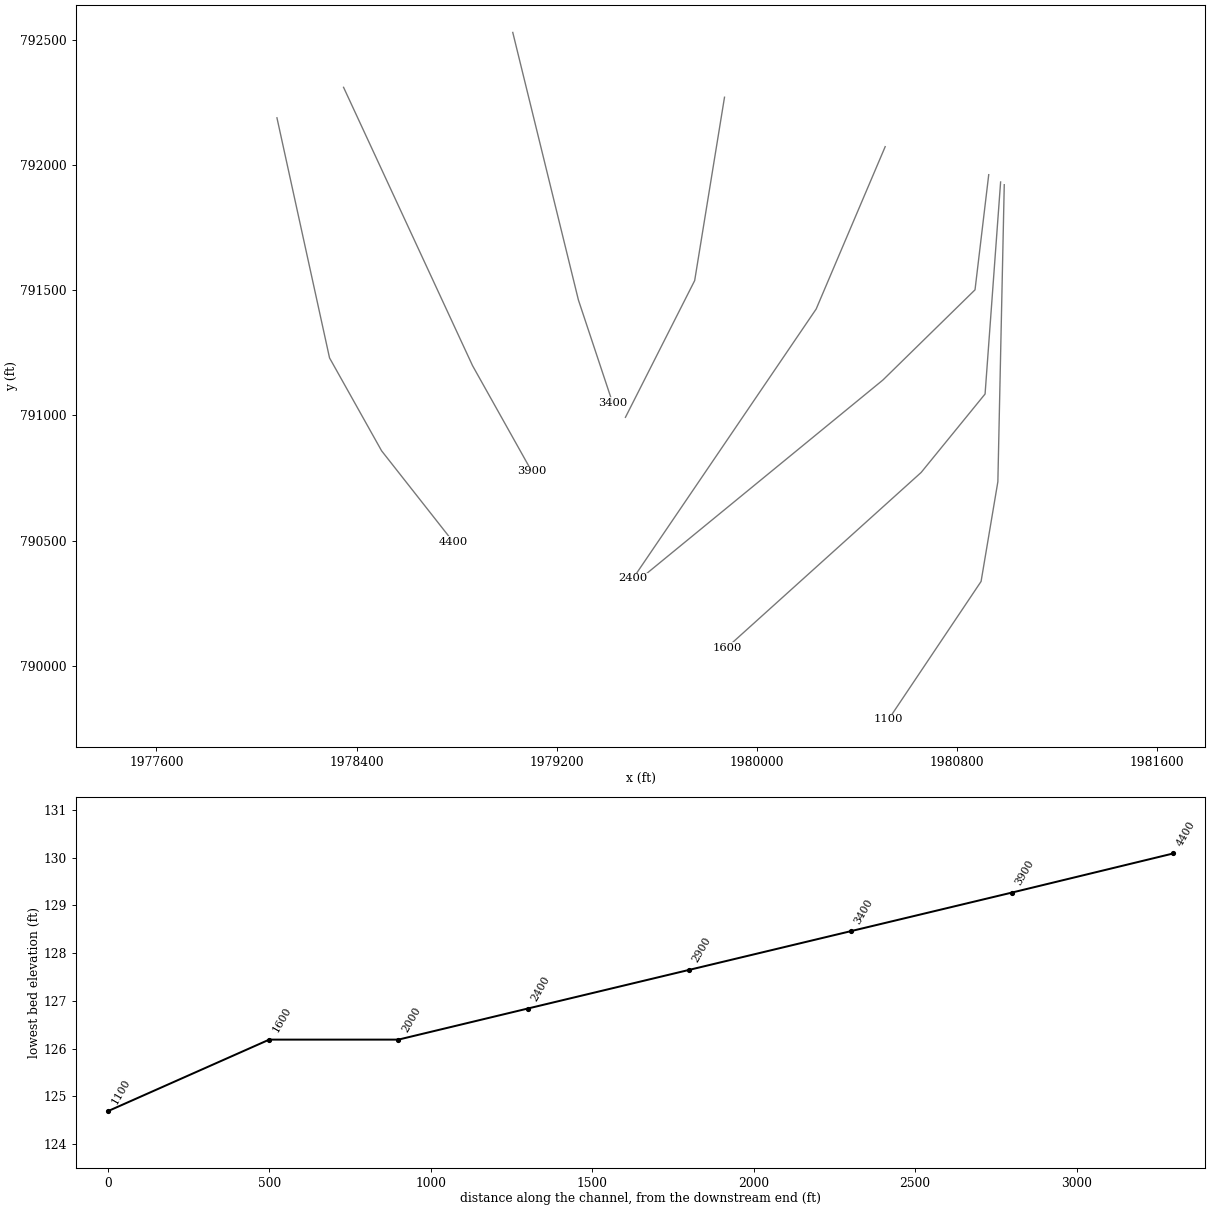
HEC-RAS study CCR_SALUDA_RIVER.prj: CCR SALUDA RIVER Detailed Study

--- CCR_SALUDA_RIVER.g01 (geometry) --- (continued)

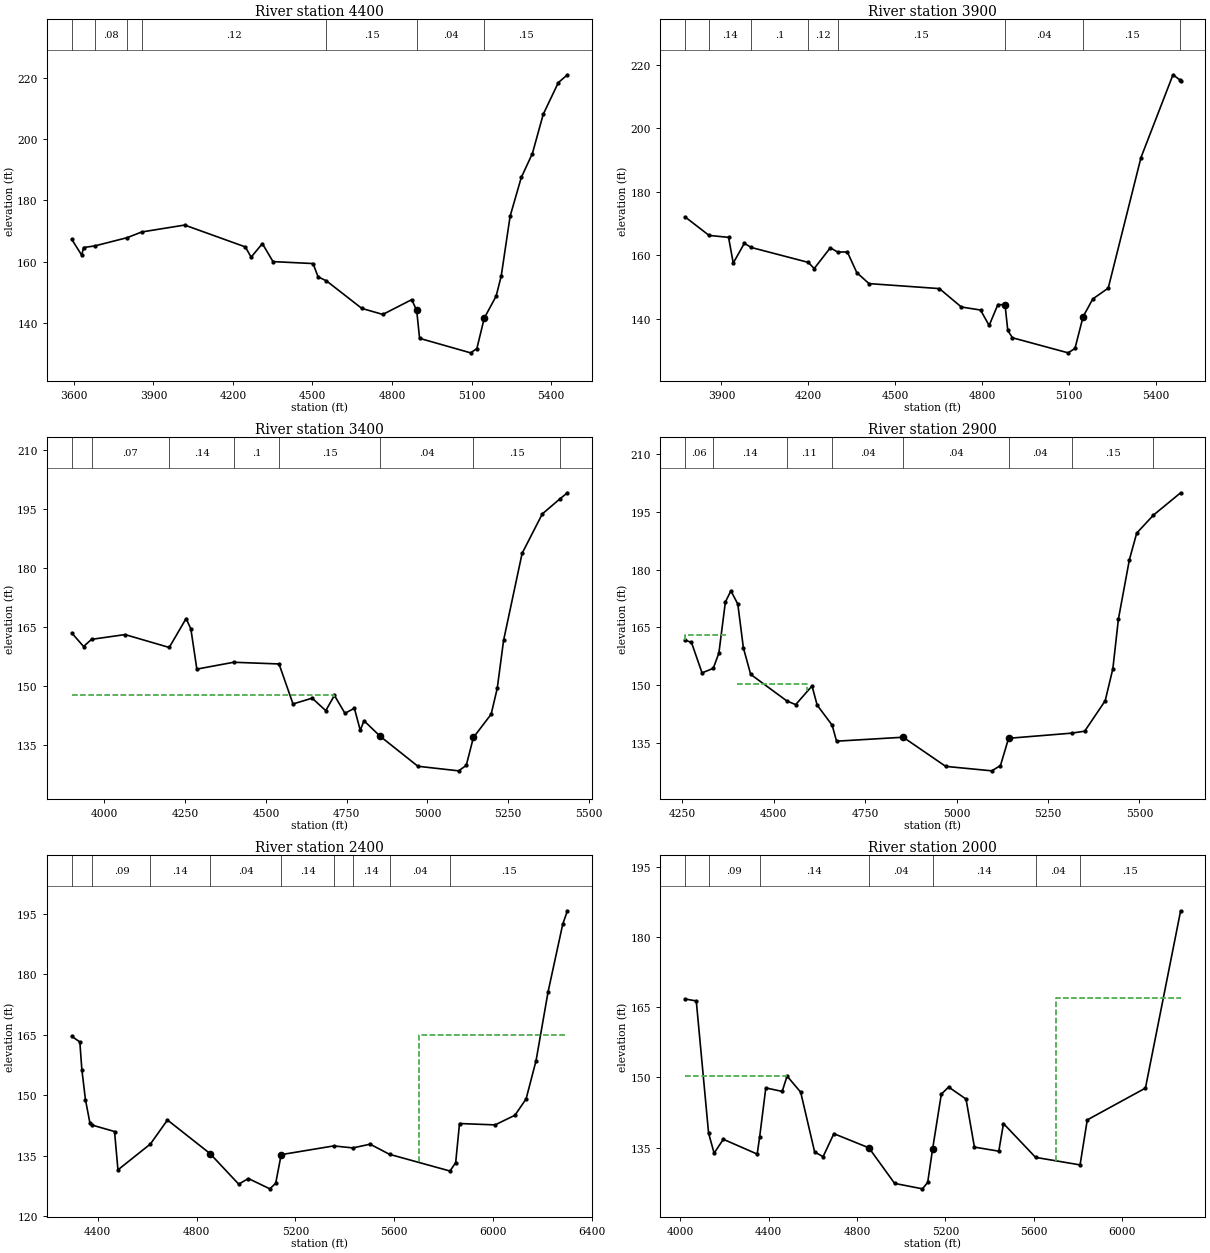
Type RM Length L Ch R = 1 ,4400    ,514,500,484
BEGIN DESCRIPTION:
SALUDA RIVER 9.0
END DESCRIPTION:
XS GIS Cut Line= 4
      1978081.87       792189.71      1978292.06       791230.15
      1978500.08       790858.87      1978785.55         790496.
#Sta/Elev= 30
  3592.1  167.26  3629.8  162.04  3636.5  164.59  3678.2  165.09  3801.3  167.82
  3856.1  169.68    4018  171.94  4246.9  164.78  4268.6  161.42  4311.1  165.86
  4351.2  159.97  4502.4  159.33  4521.2  154.97  4552.7  153.67  4686.2  144.64
  4765.4  142.67  4874.5  147.51  4893.2  143.98  4904.1  134.84  5096.4  130.09
  5120.1  131.47  5148.1  141.46    5193  148.69    5212  155.23  5245.6  174.84
  5287.7  187.52  5329.6  195.37  5370.5  208.22  5427.4  218.59  5461.7  221.16
#Mann= 7 ,-1,0
  3592.1     .14       0  3678.2     .08       0  3801.3      .1       0
  3856.1     .12       0  4552.7     .15       0  4893.2     .04       0
  5148.1     .15       0
Bank Sta=4893.2,5148.1
XS Rating Curve= 0 ,0
Exp/Cntr=0.3,0.1

Type RM Length L Ch R = 1 ,3900    ,545,500,485
BEGIN DESCRIPTION:
SALUDA RIVER 8.0
END DESCRIPTION:
XS GIS Cut Line= 3
      1978348.12       792311.51      1978863.56       791199.24
       1979100.5       790776.28
#Sta/Elev= 30
  3774.1  172.08  3857.2  166.23  3924.5  165.62  3940.6  157.53    3979  163.74
    4003  162.43  4199.7  157.74  4220.1   155.8  4275.6  162.33  4300.8  161.01
  4334.5  161.02    4367  154.53  4409.2  151.06  4652.2  149.49  4727.9   143.7
  4794.1  142.74  4823.9  137.88  4854.1  144.48  4878.8  144.36  4888.2  136.34
  4904.1  134.02  5096.4  129.27  5120.1  130.65  5148.1  140.64  5181.6  146.23
  5234.9  149.64    5348  190.75  5458.4  216.79  5483.6  215.08  5484.8  214.97
#Mann= 8 ,-1,0
  3774.1     .07       0  3857.2     .14       0    4003      .1       0
  4199.7     .12       0  4300.8     .15       0  4878.8     .04       0
  5148.1     .15       0  5483.6     .11       0
Bank Sta=4878.8,5148.1
XS Rating Curve= 0 ,0
Exp/Cntr=0.3,0.1

Type RM Length L Ch R = 1 ,3400    ,568,500,286
BEGIN DESCRIPTION:
SALUDA RIVER 7.0
END DESCRIPTION:
XS GIS Cut Line= 3
      1979024.36       792530.86      1979286.73       791461.47
      1979423.42        791050.4
#Sta/Elev= 30
  3898.9  163.48  3935.5  160.04  3960.1  161.86  4063.8  163.07  4200.6   159.8
  4252.8  167.14  4267.6  164.53  4286.1   154.3  4400.1  156.04  4540.5  155.61
  4583.8  145.45  4643.1  146.92  4685.2  143.75    4712  147.62  4744.5  143.08
  4773.8  144.35    4792  138.75  4803.5  141.18  4854.1  137.21  4970.4  129.62
  5096.4  128.46  5120.1  129.84  5142.2  136.93  5197.1  142.83    5216  149.41
  5235.7  161.63    5293  183.71  5355.5  193.72  5409.6  197.51  5433.2  199.09
#Mann= 8 ,-1,0
  3898.9     .06       0  3960.1     .07       0  4200.6     .14       0
  4400.1      .1       0  4540.5     .15       0  4854.1     .04       0
  5142.2     .15       0  5409.6     .11       0
#XS Ineff= 2 , 0
       0    4710  147.65               0
Permanent Ineff=
       F       F
Bank Sta=4854.1,5142.2
XS Rating Curve= 0 ,0
Exp/Cntr=0.3,0.1

Type RM Length L Ch R = 1 ,2900    ,561,500,633
BEGIN DESCRIPTION:
SALUDA RIVER 6.0
END DESCRIPTION:
XS GIS Cut Line= 3
      1979870.59       792271.95      1979751.35       791539.18
      1979474.64       790992.64
#Sta/Elev= 30
  4257.6  161.67  4275.2   161.1  4304.2  153.15  4334.9  154.33  4350.3  158.33
    4368  171.59  4383.1  174.51    4402  171.06  4417.2  159.69  4437.1  152.77
  4535.7  145.87  4560.2  144.88  4604.9  149.74  4618.9  144.76    4660  139.52
  4671.9  135.37  4854.1   136.4  4970.4  128.81  5096.4  127.65  5120.1  129.03
  5142.2  136.12  5314.5  137.46  5350.3  137.97  5406.3  145.88  5427.3  154.22
  5442.5  167.15  5472.5  182.61  5492.5  189.53  5538.3  194.22  5612.6  200.03
#Mann= 8 ,-1,0
  4257.6     .06       0  4334.9     .14       0  4535.7     .11       0
    4660     .04       0  4854.1     .04       0  5142.2     .04       0
  5314.5     .15       0  5538.3     .11       0
#XS Ineff= 2 ,-1
    4250    4370     163    4400  4592.3  150.15
Permanent Ineff=
       F       F
Bank Sta=4854.1,5142.2
XS Rating Curve= 0 ,0
Exp/Cntr=0.3,0.1

Type RM Length L Ch R = 1 ,2400    ,496,400,119
BEGIN DESCRIPTION:
SALUDA RIVER 5.0
END DESCRIPTION:
XS GIS Cut Line= 3
      1980512.75       792074.32      1980236.87       791425.43
      1979505.82       790349.97
#Sta/Elev= 30
  4294.9  164.63  4327.6  163.22  4335.8  156.33  4350.3  148.93  4368.6  143.08
  4378.5  142.61    4468  141.04  4481.8  131.54  4613.2  137.95  4682.1  143.89
  4854.1  135.59  4970.4     128  5009.7  129.39  5096.4  126.84  5120.1  128.22
  5142.2  135.31  5354.8  137.47  5432.1  136.98  5502.2   137.9  5580.6  135.39
  5825.4  131.25  5848.4  133.36  5863.8  143.02  6007.7  142.68  6088.1  145.07
  6133.3  149.12  6173.6   158.6  6222.2  175.65  6281.5   192.4  6300.4  195.72
#Mann= 9 ,-1,0
  4294.9     .06       0  4378.5     .09       0  4613.2     .14       0
  4854.1     .04       0  5142.2     .14       0  5354.8     .04       0
  5432.1     .14       0  5580.6     .04       0  5825.4     .15       0
#XS Ineff= 2 , 0
       0                    5700       0     165
Permanent Ineff=
       F       F
Bank Sta=4854.1,5142.2
XS Rating Curve= 0 ,0
Exp/Cntr=0.3,0.1

Type RM Length L Ch R = 1 ,2000    ,391,400,436
BEGIN DESCRIPTION:
SALUDA RIVER 4.0
END DESCRIPTION:
XS GIS Cut Line= 4
      1980926.55       791962.41      1980871.77       791502.24
      1980503.74       791141.86      1979525.11       790340.31
#Sta/Elev= 30
  4021.5  166.73  4072.6  166.31  4128.3  138.09  4153.3  133.81  4195.1  136.77
  4348.4  133.61  4359.7  137.36  4387.3  147.74  4461.4  146.99  4483.6  150.26
  4545.2  146.83  4608.3  134.07  4646.5  133.05  4695.4  137.97  4854.1  134.94
  4970.4  127.35  5096.4  126.19  5120.1  127.57  5142.2  134.66  5181.7  146.39
  5214.8  147.93  5293.6  145.36  5331.6   135.1  5441.9  134.23  5463.1  140.13
  5608.4  132.91  5809.8   131.3  5842.4  140.91  6105.7   147.7    6265  185.56
#Mann= 7 ,-1,0
  4021.5     .06       0  4128.3     .09       0  4359.7     .14       0
  4854.1     .04       0  5142.2     .14       0  5608.4     .04       0
  5809.8     .15       0
#XS Ineff= 2 , 0
       0  4483.6   150.3    5700       0     167
Permanent Ineff=
       F       F
Bank Sta=4854.1,5142.2
XS Rating Curve= 0 ,0
Exp/Cntr=0.3,0.1

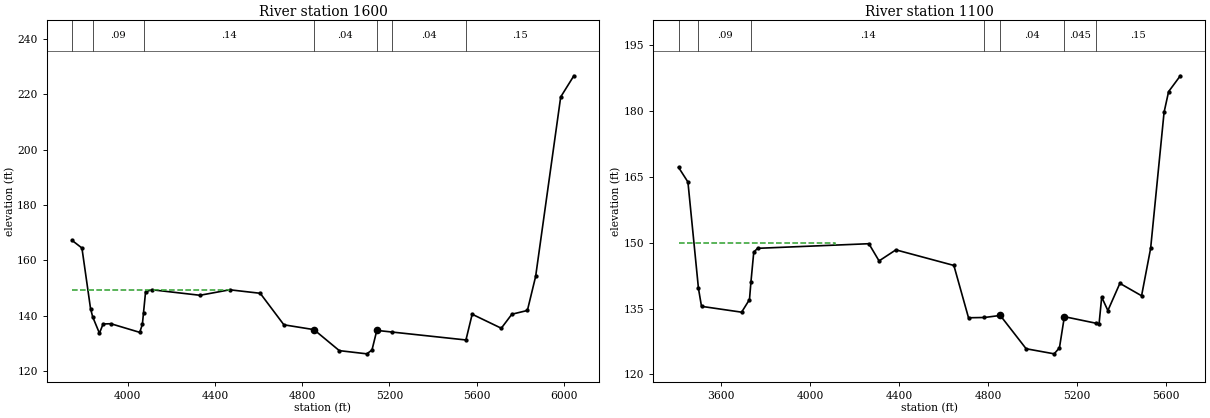
Type RM Length L Ch R = 1 ,1600    ,406,500,615
BEGIN DESCRIPTION:
SALUDA RIVER 3.0
END DESCRIPTION:
XS GIS Cut Line= 4
      1980974.03       791933.21      1980911.94       791085.89
      1980656.51       790772.36      1979880.37       790072.62
#Sta/Elev= 30
    3746  167.18  3791.2  164.42  3830.6  142.56  3840.4  139.56  3871.4  133.64
  3888.2  136.98  3923.8  137.07    4056  133.95  4068.1  136.85  4073.3  141.01
  4082.9  148.68  4113.3  149.33  4332.1  147.35  4468.4  149.33    4608  148.07
  4716.5  136.68  4854.1  134.94  4970.4  127.35  5096.4  126.19  5120.1  127.57
  5142.2  134.66  5212.6  134.06  5550.6   131.2  5579.1   140.5  5712.5  135.44
  5760.9   140.5  5832.1  141.86  5869.9  154.17  5984.7  219.01    6045  226.66
#Mann= 7 ,-1,0
    3746     .06       0  3840.4     .09       0  4073.3     .14       0
  4854.1     .04       0  5142.2     .14       0  5212.6     .04       0
  5550.6     .15       0
#XS Ineff= 2 , 0
       0  4468.4  149.35               0
Permanent Ineff=
       F       F
Bank Sta=4854.1,5142.2
XS Rating Curve= 0 ,0
Exp/Cntr=0.3,0.1

Type RM Length L Ch R = 1 ,1100    ,576,500,474
BEGIN DESCRIPTION:
SALUDA RIVER 2.0
END DESCRIPTION:
XS GIS Cut Line= 4
      1980988.64       791922.27      1980963.07       790735.28
      1980895.99       790336.75      1980526.61       789785.94
#Sta/Elev= 30
  3408.6  167.18  3450.8  163.84  3498.1   139.6  3511.8  135.51    3692  134.18
  3727.4  137.06  3733.9  141.06  3746.6  147.86  3763.7  148.73  4263.8  149.78
  4309.6  145.86  4385.2  148.38  4645.7  144.83  4711.5  132.91  4783.3  132.97
  4854.1  133.44  4970.4  125.85  5096.4  124.69  5120.1  126.07  5142.2  133.16
  5285.6  131.65  5298.1  131.52  5309.9  137.61  5337.7  134.55  5391.6  140.75
  5489.1  137.92  5529.8  148.73  5590.2  179.73  5610.5  184.43  5663.2  188.04
#Mann= 7 ,-1,0
  3408.6     .06       0  3498.1     .09       0  3733.9     .14       0
  4783.3    .045       0  4854.1     .04       0  5142.2    .045       0
  5285.6     .15       0
#XS Ineff= 2 , 0
       0  4112.5   149.9               0
Permanent Ineff=
       F       F
Bank Sta=4854.1,5142.2
XS Rating Curve= 0 ,0
Exp/Cntr=0.3,0.1
LCMann Table=0

Chan Stop Cuts=-1
Use User Specified Reach Order=0
Composite Channel Slope=5

--- CCR_SALUDA_RIVER.g02 (geometry) ---

Geom Title=Ex_con_with added
Program Version=6.10

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
River Reach=SALUDA RIVER    ,Reach-1

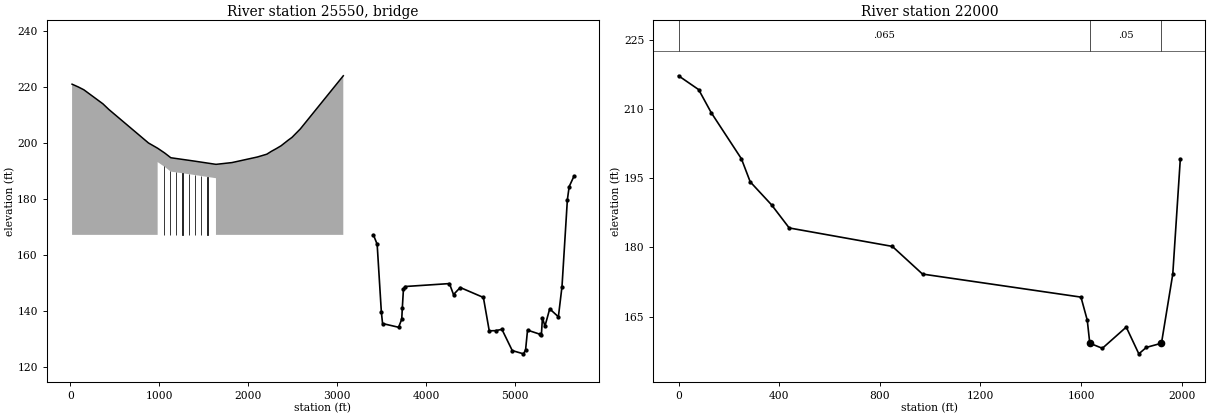
Type RM Length L Ch R = 3 ,25550   ,,,
Bridge Culvert--1,0,-1,-1, 0
Deck Dist Width WeirC Skew NumUp NumDn MinLoCord MaxHiCord MaxSubmerge Is_Ogee
95,108,2.5,0, 25, 26, 191.32, , 0.98, 0, 5.8,5.8,,
    19.5    90.2     152     366     399     432     879     982     982    1061
    1130    1391    1638    1638  1817.7    2104    2210    2260    2317    2370
    2410    2450    2493    2586    3070
     221     220     219     214     213     212     200 198.123 198.123 196.426
  194.73  193.55  192.37  192.37     193     195     196     197     198     199
     200     201     202     205     224
                                                                 193.173 191.476
  189.78   188.6  187.42
                                        
       0   167.5   238.2     300     514     547     580    1027    1130    1130
    1209    1278    1539    1786    1786  1965.7    2252    2358    2408    2465
    2518    2558    2598    2641    2734    3218
     222     221     220     219     214     213     212     200 198.123 198.123
 196.426  194.73  193.55  192.37  192.37     193     195     196     197     198
     199     200     201     202     205     224
                                                                         193.173
 191.476  189.78   188.6  187.42
                                                
Pier Skew, UpSta & Num, DnSta & Num=  ,1052, 2 ,1200, 2 , 0 , 0 , 0 ,,
     3.5     3.5
   156.9   192.2
     3.5     3.5
   156.9   192.2
Pier Skew, UpSta & Num, DnSta & Num=  ,1122, 2 ,1270, 2 , 0 , 0 , 0 ,,
     3.5     3.5
   156.9   192.2
     3.5     3.5
   156.9   192.2
Pier Skew, UpSta & Num, DnSta & Num=  ,1192, 2 ,1340, 2 , 0 , 0 , 0 ,,
     3.5     3.5
   156.9   192.2
     3.5     3.5
   156.9   192.2
Pier Skew, UpSta & Num, DnSta & Num=  ,1262, 2 ,1410, 2 , 0 , 0 , 0 ,,
     3.5     3.5
   156.9 193.173
     3.5     3.5
   156.9   192.2
Pier Skew, UpSta & Num, DnSta & Num=  ,1332, 2 ,1480, 2 , 0 , 0 , 0 ,,
     3.5     3.5
   156.9   192.2
     3.5     3.5
   156.9   192.2
Pier Skew, UpSta & Num, DnSta & Num=  ,1402, 2 ,1550, 2 , 0 , 0 , 0 ,,
     3.5     3.5
   156.9   192.2
     3.5     3.5
   156.9   192.2
Pier Skew, UpSta & Num, DnSta & Num=  ,1472, 2 ,1620, 2 , 0 , 0 , 0 ,,
     3.5     3.5
   156.9   192.2
     3.5     3.5
   156.9   192.2
Pier Skew, UpSta & Num, DnSta & Num=  ,1542, 2 ,1690, 2 , 0 , 0 , 0 ,,
     3.5     3.5
   156.9   192.2
     3.5     3.5
   156.9   192.2
Abutment Skew #Up #Dn= , 3 , 3
     982     986    1020
 191.173 191.173 174.173
    1130    1134    1168
 191.173 191.173 174.173
Abutment Skew #Up #Dn= , 3 , 3
    1542    1634    1638
  139.42  185.42  185.42
    1692    1784    1786
  139.42  185.42  185.42
BR Coef= 0 , 0 , 1 ,1.25, 0 ,,,1.3,0,,2,191.42
WSPro=,,,, 1 ,,,, 0 ,,,, 0 ,,,,-1 ,-1 ,-1 , 0 , 0 , 0 , 0 , 0
BC Design=,, 0 ,, 0 ,,,,,,
BC Use User HTab Curves=0
BC User HTab FreeFlow(D)= 0

Type RM Length L Ch R = 1 ,22000   ,3200,3200,3200
BEGIN DESCRIPTION:
FEMA XS: I
END DESCRIPTION:
XS GIS Cut Line= 2
     1964713.343      798155.587     1964453.567      796811.327
#Sta/Elev= 19
       0  217.22      80  214.22     130  209.22     250  199.22     285  194.22
     370  189.22     440  184.22     850  180.22     970  174.22    1600  169.22
    1625  164.22    1635  159.22    1685  158.12    1780  162.72    1830  156.92
    1860  158.32    1920  159.22    1965  174.22    1995  199.22
#Mann= 3 ,0,0
       0    .065       0    1635     .05       0    1920    .065       0
Bank Sta=1635,1920
XS Rating Curve= 0 ,0
Exp/Cntr=0.3,0.1