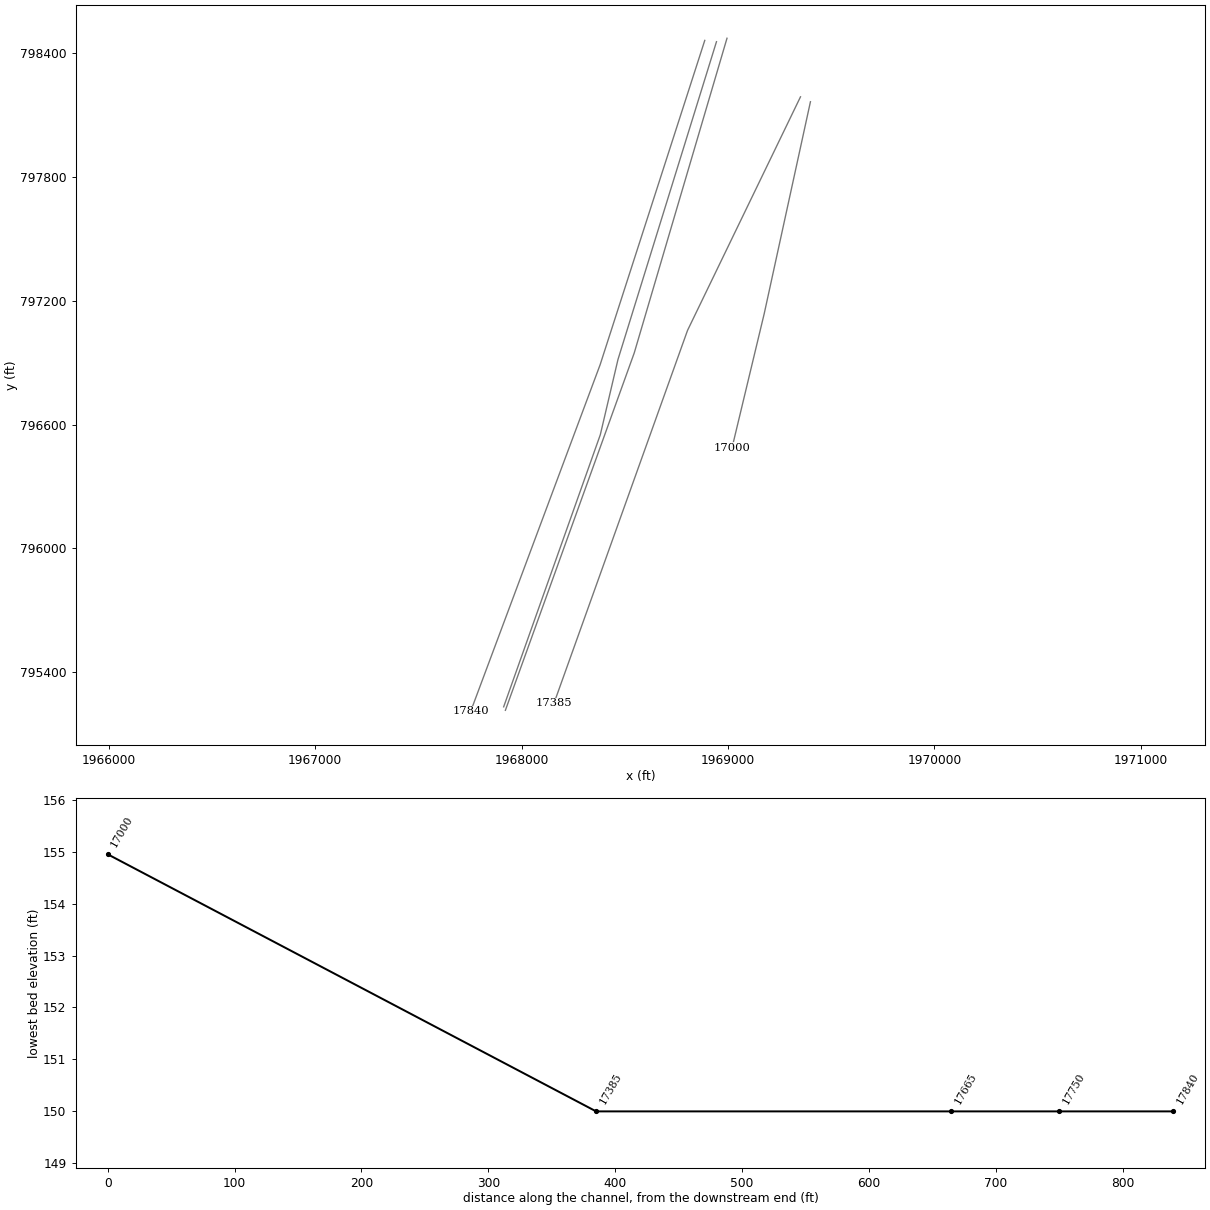
HEC-RAS study CCR_SALUDA_RIVER.prj: CCR SALUDA RIVER Detailed Study

--- CCR_SALUDA_RIVER.g02 (geometry) --- (continued)

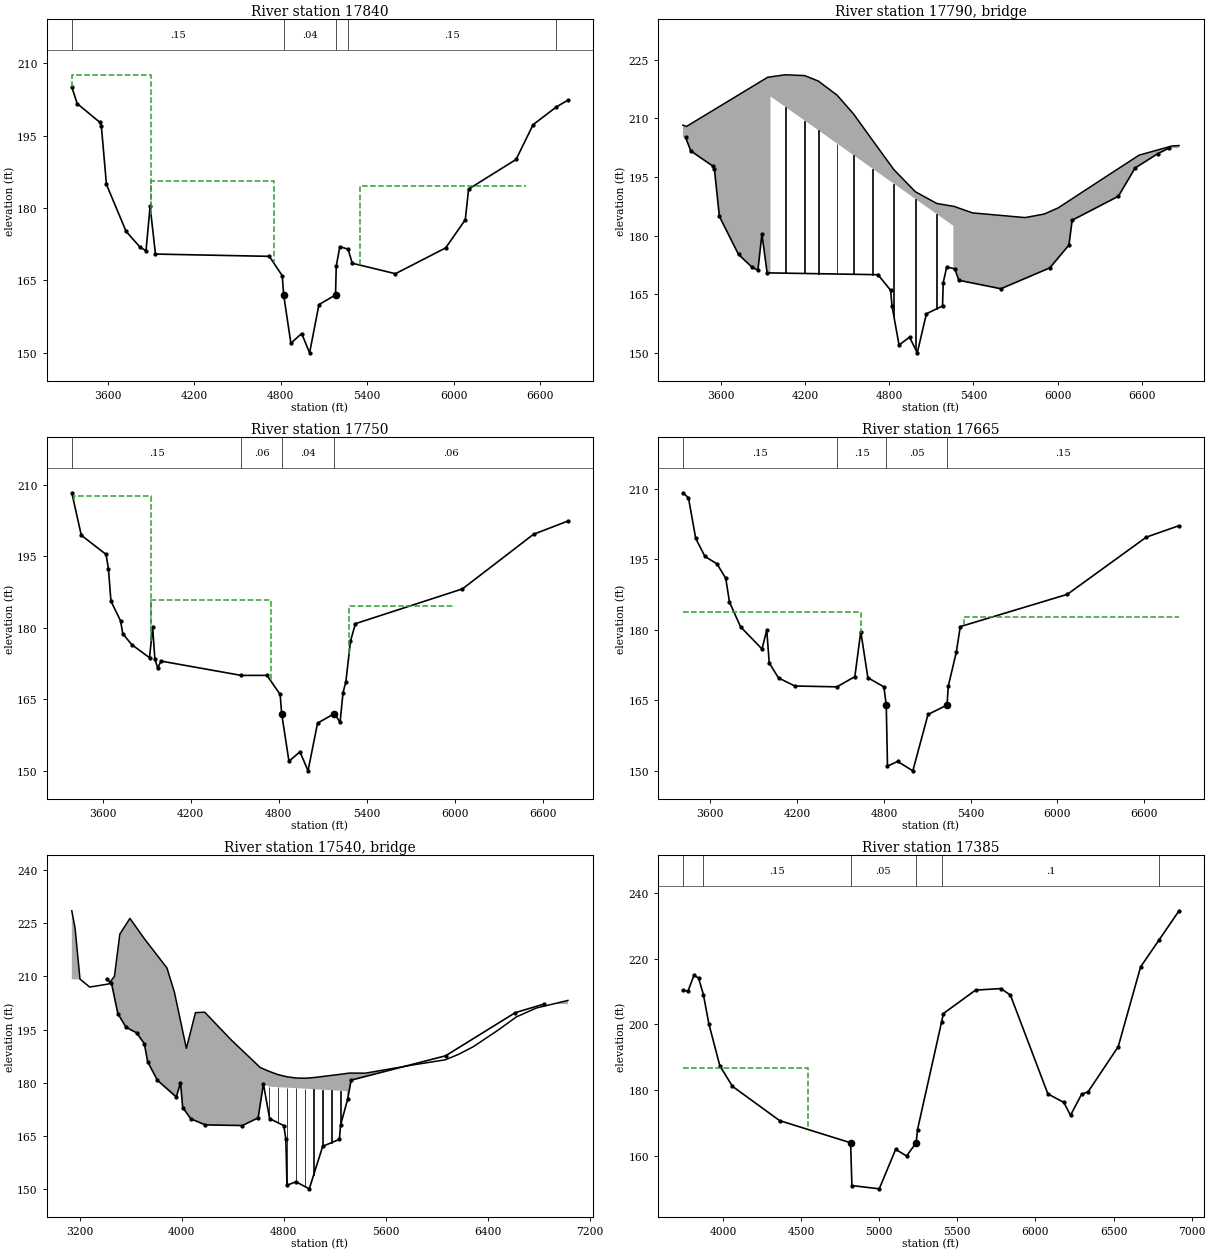
Type RM Length L Ch R = 1 ,17840   ,77,90,170
BEGIN DESCRIPTION:
SALUDA RIVER (I-26 Ramp - US)
END DESCRIPTION:
XS GIS Cut Line= 3
       1968887.4       798461.11      1968380.66       796890.12
      1967753.47       795210.18
#Sta/Elev= 30
  3349.3  205.13  3386.2  201.67  3545.5  197.74  3554.5  197.01  3589.8  184.91
  3726.1  175.18  3822.5  171.92  3864.5  171.14  3892.9   180.4    3930  170.47
    4720     170    4810     166    4820     162    4870     152    4945     154
    5000     150    5065     160    5180     162    5185     168    5210     172
  5267.1  171.49  5296.2  168.57  5595.7   166.4  5944.6  171.75  6080.7  177.59
  6103.7  183.94  6433.2  190.08  6551.5  197.29  6712.6  200.96  6793.2  202.38
#Mann= 5 ,-1,0
  3349.3     .15       0    4820     .04       0    5180     .04       0
  5267.1     .15       0  6712.6     .11       0
#XS Ineff= 3 ,-1
    3300    3900  207.63  3900.1    4750   185.7    5350    6500  184.62
Permanent Ineff=
       F       F       F
Bank Sta=4820,5180
XS Rating Curve= 0 ,0
Exp/Cntr=0.5,0.3

Type RM Length L Ch R = 3 ,17790   ,,,
BEGIN DESCRIPTION:
SALUDA RIVER (I-26 Ramp - TOR)
Structure ID: I-26 Ramp
Detailed Survey Structure
END DESCRIPTION:
Bridge Culvert--1,0,-1,-1, 0
Deck Dist Width WeirC Skew NumUp NumDn MinLoCord MaxHiCord MaxSubmerge Is_Ogee
32.5,35,3,0, 25, 25, , , 0.95, 0, 1,1,,
  3329.9  3354.9  3934.1  3954.1  3954.1  4059.4  4197.7  4295.9  4428.4    4545
    4680    4833    4986    5139    5257    5257    5262  5393.9  5767.8  5903.8
  6004.1    6281  6580.6  6813.7  6865.3
   208.3  207.93  220.54  220.64  220.64  221.17  220.96  219.54  215.95  211.19
  204.47   196.9  191.24  188.23  187.51  187.51  187.48  185.82  184.62  185.52
   187.1  193.61   200.6  202.94  203.05
     130     130     130     130  215.64  212.96  209.45  206.95  203.58  200.61
  197.18  193.29   189.4  185.51  182.51     130     130     130     130     130
     130     130     130     130     130
  3329.9  3354.9  3934.1  3954.1  3954.1  4059.4  4197.7  4295.9  4428.4    4545
    4680    4833    4986    5139    5257    5257    5262  5393.9  5767.8  5903.8
  6004.1    6281  6580.6  6813.7  6865.3
   208.3  207.93  220.54  220.64  220.64  221.17  220.96  219.54  215.95  211.19
  204.47   196.9  191.24  188.23  187.51  187.51  187.48  185.82  184.62  185.52
   187.1  193.61   200.6  202.94  203.05
     130     130     130     130  215.64  212.96  209.45  206.95  203.58  200.61
  197.18  193.29   189.4  185.51  182.51     130     130     130     130     130
     130     130     130     130     130
Pier Skew, UpSta & Num, DnSta & Num=  ,4059.4, 2 ,4059.4, 2 , 0 , 0 , 0 ,0,0
       5       5
   194.5  212.96
       5       5
   194.5  212.96
Pier Skew, UpSta & Num, DnSta & Num=  ,4197.7, 2 ,4197.7, 2 , 0 , 0 , 0 ,0,0
       5       5
  192.72  209.45
       5       5
  192.72  209.45
Pier Skew, UpSta & Num, DnSta & Num=  ,4295.9, 2 ,4295.9, 2 , 0 , 0 , 0 ,0,0
       5       5
     177  206.95
       5       5
     177  206.95
Pier Skew, UpSta & Num, DnSta & Num=  ,4428.4, 2 ,4428.4, 2 , 0 , 0 , 0 ,0,0
       5       5
     168  203.58
       5       5
     168  203.58
Pier Skew, UpSta & Num, DnSta & Num=  ,4545, 2 ,4545, 2 , 0 , 0 , 0 ,0,0
       5       5
     168  200.62
       5       5
     168  200.62
Pier Skew, UpSta & Num, DnSta & Num=  ,4680, 2 ,4680, 2 , 0 , 0 , 0 ,0,0
       5       5
     168  197.18
       5       5
     168  197.18
Pier Skew, UpSta & Num, DnSta & Num=  ,4833, 2 ,4833, 2 , 0 , 0 , 0 ,0,0
       5       5
     156  193.29
       5       5
     156  193.29
Pier Skew, UpSta & Num, DnSta & Num=  ,4986, 2 ,4986, 2 , 0 , 0 , 0 ,0,0
       5       5
     150   189.4
       5       5
     150   189.4
Pier Skew, UpSta & Num, DnSta & Num=  ,5139, 2 ,5139, 2 , 0 , 0 , 0 ,0,0
       5       5
     160  185.51
       5       5
     160  185.51
BR Coef= 1 , 1 , 0 ,1.25, 0 ,,,0.8,0,2,0,
WSPro=,,,, 1 ,,,, 0 ,,,, 0 ,,,,-1 ,-1 ,-1 , 0 , 0 , 0 , 0 , 0
BC Design=,, 0 ,, 0 ,,,,,,
BC HTab HWMax=205.13
BC Use User HTab Curves=0
BC User HTab FreeFlow(D)= 0

Type RM Length L Ch R = 1 ,17750   ,67,85,34
BEGIN DESCRIPTION:
SALUDA RIVER (I-26 Ramp - DS)
END DESCRIPTION:
XS GIS Cut Line= 4
      1968944.07       798454.82      1968467.06       796915.33
      1968381.51       796550.92      1967913.41       795232.68
#Sta/Elev= 30
  3388.3  208.27  3453.1  199.38  3622.1  195.35  3638.3  192.33  3655.6  185.56
  3721.3  181.41  3736.2  178.72  3797.8  176.44  3918.8  173.71  3939.8  180.09
  3955.3  173.41  3974.8  171.54  3996.8     173  4544.2     170    4720     170
    4810     166    4820     162    4870     152    4945     154    5000     150
    5065     160    5180     162  5218.6  160.15  5238.6  166.36  5258.2  168.68
  5289.6  177.18  5323.3  180.84  6053.8  188.13  6538.3  199.57  6773.2  202.35
#Mann= 4 ,-1,0
  3388.3     .15       0  4544.2     .06       0    4820     .04       0
    5180     .06       0
#XS Ineff= 3 ,-1
    3400    3930  207.63  3930.1    4750   185.7  5279.5    6000  184.62
Permanent Ineff=
       F       F       F
Bank Sta=4820,5180
XS Rating Curve= 0 ,0
Exp/Cntr=0.5,0.3

Type RM Length L Ch R = 1 ,17665   ,289,280,372
BEGIN DESCRIPTION:
SALUDA RIVER (I-26 - US)
END DESCRIPTION:
XS GIS Cut Line= 3
      1968995.05       798471.57      1968545.83       796947.19
      1967921.81       795215.91
#Sta/Elev= 30
  3410.8  209.19  3449.3  208.12  3499.3  199.48  3563.3  195.63  3646.7  194.05
  3706.9  190.99  3732.8  185.92    3809  180.68  3957.6  175.93  3990.3  179.95
  4007.6  172.97  4071.7  169.77  4184.8  168.06  4475.5  167.88  4599.3  170.05
  4640.4  179.64  4689.3  169.82  4800.2  167.87  4816.4     164    4825     151
    4895     152    5000     150    5105     162  5236.4     164    5245     168
  5300.6  175.27    5328   180.7    6068  187.57  6614.2  199.75  6840.3  202.19
#Mann= 4 ,-1,0
  3410.8     .15       0  4475.5     .15       0  4816.4     .05       0
  5236.4     .15       0
#XS Ineff= 2 , 0
       0  4641.5  183.88  5356.5       0  182.67
Permanent Ineff=
       F       F
Bank Sta=4816.4,5236.4
XS Rating Curve= 0 ,0
Exp/Cntr=0.5,0.3

Type RM Length L Ch R = 3 ,17540   ,,,
BEGIN DESCRIPTION:
SALUDA RIVER (I-26 - TOR)
Structure ID: I-26
Detailed Survey Structure
END DESCRIPTION:
Bridge Culvert--1,0,-1,-1, 0
Deck Dist Width WeirC Skew NumUp NumDn MinLoCord MaxHiCord MaxSubmerge Is_Ogee
61.5,127,3,0, 39, 39, , , 0.95, 0, 1,1,,
  3138.1  3163.5  3202.5  3278.6  3427.1  3472.6  3514.7  3593.8  3707.5  3884.3
  3942.5  4036.5  4107.7  4180.1  4387.1    4615    4635    4635    4685    4755
    4825    4895    4965    5035    5105    5175    5245    5295    5295    5315
  5438.9  5814.8  6066.9  6170.9  6286.3  6482.2  6623.1  6781.7  7027.8
  228.54  223.76  209.23  206.99  207.87  210.05  221.95  226.39  220.63  212.38
  205.56  189.68  199.77  199.89   192.1  184.28  183.97  183.97  183.18  182.26
  181.65  181.31  181.24  181.43  181.74  182.05  182.36   182.6   182.6   182.7
  182.67  185.01  186.45     188  190.16  194.88  198.56  201.09  203.22
     130     130     130     130     130     130     130     130     130     130
     130     130     130     130     130     130     130  178.97  178.87  178.72
  178.58  178.43  178.29  178.14  177.99  177.85   177.7   177.6     130     130
     130     130     130     130     130     130     130     130     130
  3138.1  3163.5  3202.5  3278.6  3427.1  3472.6  3514.7  3593.8  3707.5  3884.3
  3942.5  4036.5  4107.7  4180.1  4387.1    4615    4635    4635    4685    4755
    4825    4895    4965    5035    5105    5175    5245    5295    5295    5315
  5438.9  5814.8  6066.9  6170.9  6286.3  6482.2  6623.1  6781.7  7027.8
  228.54  223.76  209.23  206.99  207.87  210.05  221.95  226.39  220.63  212.38
  205.56  189.68  199.77  199.89   192.1  184.28  183.97  183.97  183.18  182.26
  181.65  181.31  181.24  181.43  181.74  182.05  182.36   182.6   182.6   182.7
  182.67  185.01  186.45     188  190.16  194.88  198.56  201.09  203.22
     130     130     130     130     130     130     130     130     130     130
     130     130     130     130     130     130     130  178.97  178.87  178.72
  178.58  178.43  178.29  178.14  177.99  177.85   177.7   177.6     130     130
     130     130     130     130     130     130     130     130     130
Pier Skew, UpSta & Num, DnSta & Num=  ,4685, 2 ,4685, 2 , 0 , 0 , 0 ,0,0
       4       4
   163.5  178.86
       4       4
   163.5  178.86
Pier Skew, UpSta & Num, DnSta & Num=  ,4755, 2 ,4755, 2 , 0 , 0 , 0 ,0,0
       4       4
     163  178.72
       4       4
     163  178.72
Pier Skew, UpSta & Num, DnSta & Num=  ,4825, 2 ,4825, 2 , 0 , 0 , 0 ,0,0
       4       4
     149  178.57
       4       4
     149  178.57
Pier Skew, UpSta & Num, DnSta & Num=  ,4895, 2 ,4895, 2 , 0 , 0 , 0 ,0,0
       4       4
     150  178.43
       4       4
     150  178.43
Pier Skew, UpSta & Num, DnSta & Num=  ,4965, 2 ,4965, 2 , 0 , 0 , 0 ,0,0
       4       4
   148.5  178.28
       4       4
   148.5  178.28
Pier Skew, UpSta & Num, DnSta & Num=  ,5035, 2 ,5035, 2 , 0 , 0 , 0 ,0,0
       4       4
     153  178.14
       4       4
     153  178.14
Pier Skew, UpSta & Num, DnSta & Num=  ,5105, 2 ,5105, 2 , 0 , 0 , 0 ,0,0
       4       4
     160     178
       4       4
     160     178
Pier Skew, UpSta & Num, DnSta & Num=  ,5175, 2 ,5175, 2 , 0 , 0 , 0 ,0,0
       4       4
     158  177.85
       4       4
     158  177.85
Pier Skew, UpSta & Num, DnSta & Num=  ,5245, 2 ,5245, 2 , 0 , 0 , 0 ,0,0
       4       4
     166  177.71
       4       4
     166  177.71
BR Coef= 1 , 1 , 0 ,1.25, 0 ,,,0.8,0,2,0,
WSPro=,,,, 1 ,,,, 0 ,,,, 0 ,,,,-1 ,-1 ,-1 , 0 , 0 , 0 , 0 , 0
BC Design=,, 0 ,, 0 ,,,,,,
BC HTab HWMax=209.19
BC Use User HTab Curves=0
BC User HTab FreeFlow(D)= 0

Type RM Length L Ch R = 1 ,17385   ,306,385,416
BEGIN DESCRIPTION:
SALUDA RIVER (I-26 - DS)
END DESCRIPTION:
XS GIS Cut Line= 3
      1969350.99       798187.76      1968803.81         797056.
       1968156.7       795248.87
#Sta/Elev= 30
  3742.9  210.41  3774.9  210.03  3813.7  214.91  3843.2  214.07  3874.1  209.05
    3909  200.17  3979.5  187.38  4060.3  181.15  4362.4  170.73  4816.4     164
    4825     151    5000     150    5105     162    5175     160  5236.4     164
    5245     168  5399.2  200.73  5410.6  203.27  5616.7   210.4  5778.9  210.87
  5839.7  208.89  6079.7  178.85    6182  176.26  6224.5  172.35  6295.6  178.75
  6337.1  179.49    6530  193.21  6673.3  217.46    6793  225.75  6919.5  234.51
#Mann= 6 ,-1,0
  3742.9     .06       0  3874.1     .15       0  4816.4     .05       0
  5236.4     .15       0  5399.2      .1       0    6793     .11       0
#XS Ineff= 2 , 0
       0  4543.5  186.69  5386.5       0  182.42
Permanent Ineff=
       F       F
Bank Sta=4816.4,5236.4
XS Rating Curve= 0 ,0
Exp/Cntr=0.5,0.3

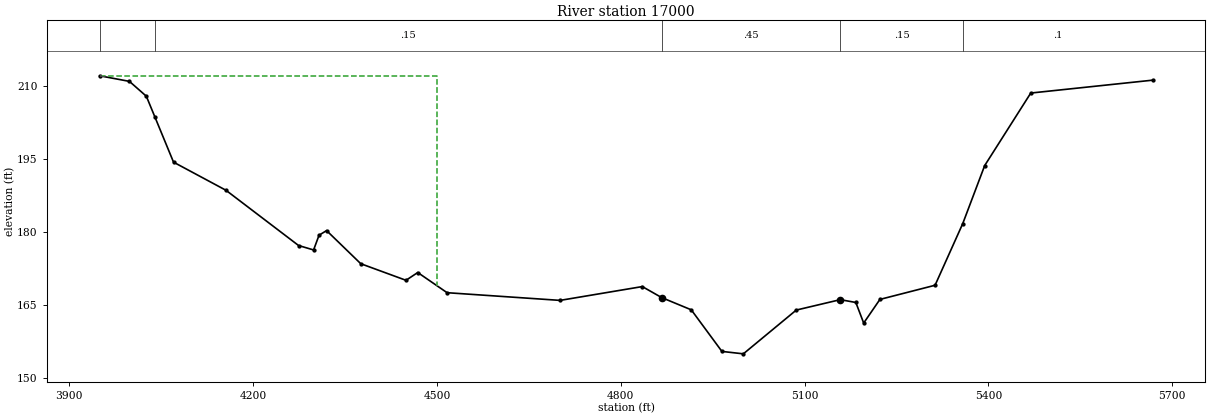
Type RM Length L Ch R = 1 ,17000   ,500,400,251
BEGIN DESCRIPTION:
SALUDA RIVER 37.0
END DESCRIPTION:
XS GIS Cut Line= 3
       1969399.2       798164.06      1969175.35       797137.59
      1969019.47       796487.82
#Sta/Elev= 30
  3949.4  212.12    3998  210.97  4025.6  207.92  4039.3  203.74    4070  194.36
  4155.6  188.58  4274.1  177.22  4298.6  176.31  4307.5  179.34  4319.8  180.29
  4375.6  173.48  4449.4  170.07  4468.6  171.67  4516.5  167.52  4700.9  165.94
  4835.1  168.78  4866.8  166.51    4915     164    4965  155.45    5000  154.95
  5086.4  163.95  5158.2  166.09  5183.6  165.51  5196.4  161.28  5222.9  166.14
  5312.9  169.05  5358.1  181.73  5393.9  193.66  5469.1  208.57  5668.2  211.22
#Mann= 5 ,-1,0
  3949.4     .06       0  4039.3     .15       0  4866.8     .45       0
  5158.2     .15       0  5358.1      .1       0
#XS Ineff= 2 , 0
       0    4500     212               0
Permanent Ineff=
       F       F
Bank Sta=4866.8,5158.2
XS Rating Curve= 0 ,0
Exp/Cntr=0.3,0.1

--- CCR_SALUDA_RIVER.g12 (geometry) ---

Geom Title=CEM
Program Version=6.10

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
River Reach=SALUDA RIVER    ,Reach-1

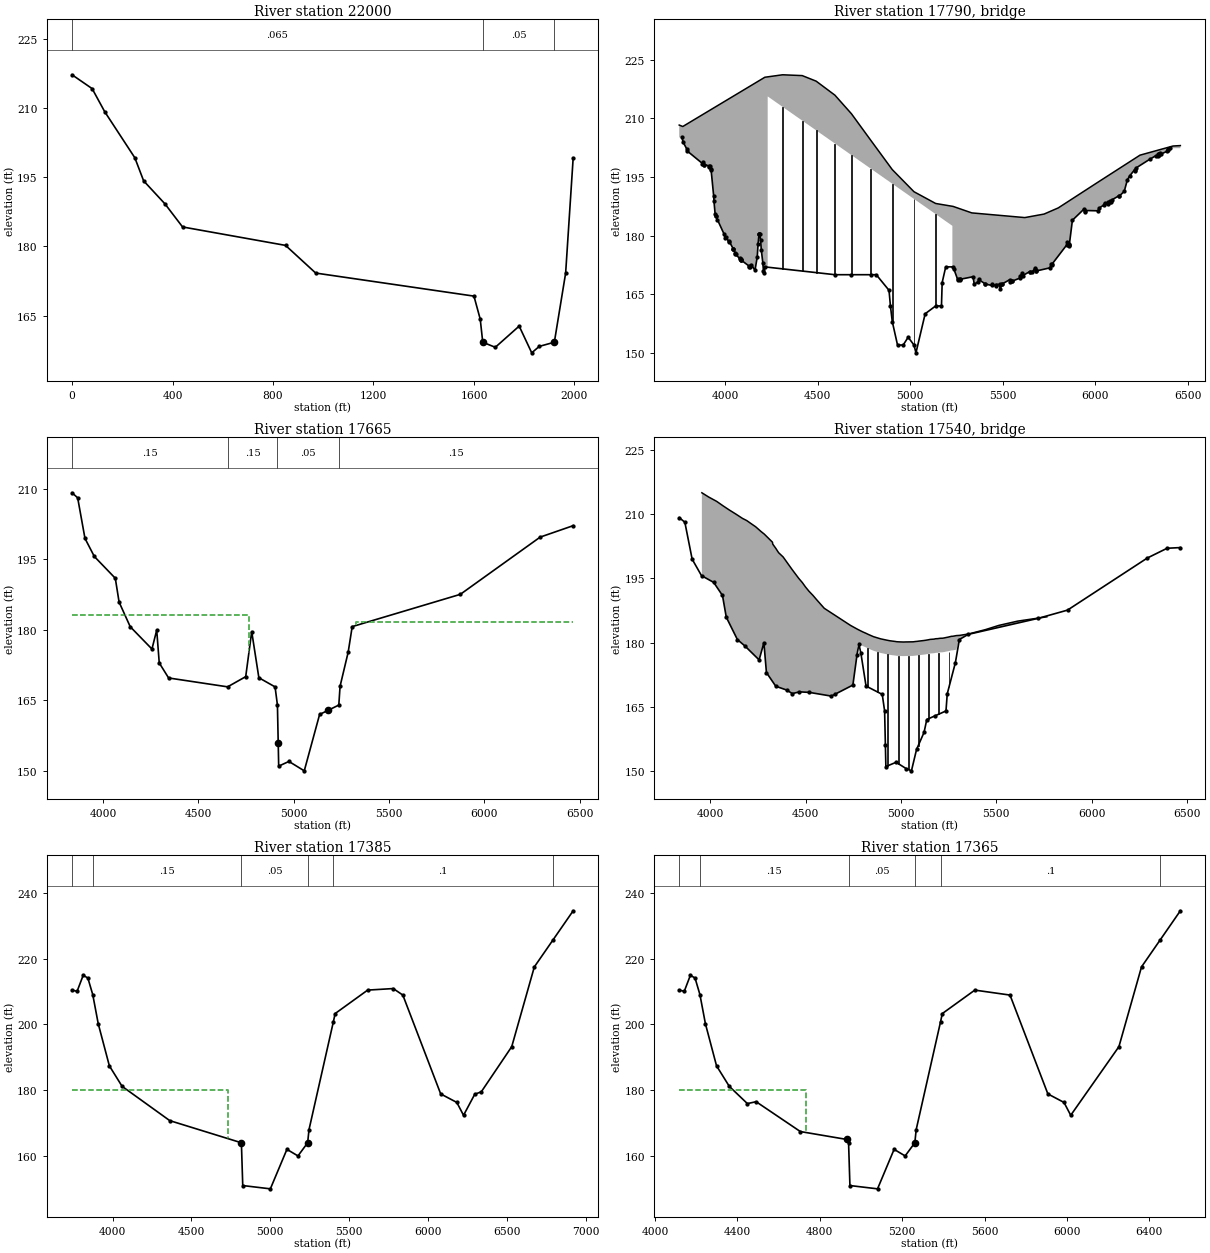
Type RM Length L Ch R = 1 ,22000   ,3200,3200,3200
BEGIN DESCRIPTION:
FEMA XS: I
END DESCRIPTION:
XS GIS Cut Line= 2
     1964713.343      798155.587     1964453.567      796811.327
#Sta/Elev= 19
       0  217.22      80  214.22     130  209.22     250  199.22     285  194.22
     370  189.22     440  184.22     850  180.22     970  174.22    1600  169.22
    1625  164.22    1635  159.22    1685  158.12    1780  162.72    1830  156.92
    1860  158.32    1920  159.22    1965  174.22    1995  199.22
#Mann= 3 ,0,0
       0    .065       0    1635     .05       0    1920    .065       0
Bank Sta=1635,1920
XS Rating Curve= 0 ,0
Exp/Cntr=0.3,0.1

Type RM Length L Ch R = 3 ,17790   ,,,
BEGIN DESCRIPTION:
SALUDA RIVER (I-26 Ramp - TOR)
Structure ID: I-26 Ramp
Detailed Survey Structure
END DESCRIPTION:
Bridge Culvert--1,0,-1,-1, 0
Deck Dist Width WeirC Skew NumUp NumDn MinLoCord MaxHiCord MaxSubmerge Is_Ogee
32.5,35,3,40, 25, 25, , , 0.95, 0, 1,1,,
3750.8513770.0024213.6964229.0164229.0164309.6814415.625 4490.854592.3514681.672
4785.0884902.2935019.4985136.7025227.0965227.0965230.9265331.9675618.3915722.573
5799.4086011.5256241.0326419.5976459.125
   208.3  207.93  220.54  220.64  220.64  221.17  220.96  219.54  215.95  211.19
  204.47   196.9  191.24  188.23  187.51  187.51  187.48  185.82  184.62  185.52
   187.1  193.61   200.6  202.94  203.05
                                  215.64  212.96  209.45  206.95  203.58  200.61
  197.18  193.29   189.4  185.51  182.51
                                        
3750.8513770.0024213.6964229.0164229.0164309.6814415.625 4490.854592.3514681.672
4785.0884902.2935019.4985136.7025227.0965227.0965230.9265331.9675618.3915722.573
5799.4086011.5256241.0326419.5976459.125
   208.3  207.93  220.54  220.64  220.64  221.17  220.96  219.54  215.95  211.19
  204.47   196.9  191.24  188.23  187.51  187.51  187.48  185.82  184.62  185.52
   187.1  193.61   200.6  202.94  203.05
                                  215.64  212.96  209.45  206.95  203.58  200.61
  197.18  193.29   189.4  185.51  182.51
                                        
Pier Skew, UpSta & Num, DnSta & Num=  ,4309.681, 2 ,4309.681, 2 , 0 , 0 , 0 ,0,0
       5       5
   194.5  212.96
       5       5
   194.5  212.96
Pier Skew, UpSta & Num, DnSta & Num=  ,4415.625, 2 ,4415.625, 2 , 0 , 0 , 0 ,0,0
       5       5
  192.72  209.45
       5       5
  192.72  209.45
Pier Skew, UpSta & Num, DnSta & Num=  ,4490.85, 2 ,4490.85, 2 , 0 , 0 , 0 ,0,0
       5       5
     177  206.95
       5       5
     177  206.95
Pier Skew, UpSta & Num, DnSta & Num=  ,4592.351, 2 ,4592.351, 2 , 0 , 0 , 0 ,0,0
       5       5
     168  203.58
       5       5
     168  203.58
Pier Skew, UpSta & Num, DnSta & Num=  ,4681.672, 2 ,4681.672, 2 , 0 , 0 , 0 ,0,0
       5       5
     168  200.62
       5       5
     168  200.62
Pier Skew, UpSta & Num, DnSta & Num=  ,4785.088, 2 ,4785.088, 2 , 0 , 0 , 0 ,0,0
       5       5
     168  197.18
       5       5
     168  197.18
Pier Skew, UpSta & Num, DnSta & Num=  ,4902.293, 2 ,4902.293, 2 , 0 , 0 , 0 ,0,0
       5       5
     156  193.29
       5       5
     156  193.29
Pier Skew, UpSta & Num, DnSta & Num=  ,5019.498, 2 ,5019.498, 2 , 0 , 0 , 0 ,0,0
       5       5
     150   189.4
       5       5
     150   189.4
Pier Skew, UpSta & Num, DnSta & Num=  ,5136.702, 2 ,5136.702, 2 , 0 , 0 , 0 ,0,0
       5       5
     160  185.51
       5       5
     160  185.51
BR Coef= 1 , 1 , 0 ,1.25, 0 ,,,0.8,0,2,0,
WSPro=,,,, 1 ,,,, 0 ,,,, 0 ,,,,-1 ,-1 ,-1 , 0 , 0 , 0 , 0 , 0
BR U #Sta/Elev= 153
 3765.71  205.13 3772.15  203.89 3792.52  202.11 3793.98  201.67 3876.33  198.46
  3878.7  198.94 3885.83  198.07 3886.36  198.17 3912.64  197.83 3914.09  197.46
 3916.01  197.74 3922.91  197.01 3923.14  196.83 3937.23  190.05 3938.53  188.92
 3944.66  185.64 3949.95  184.91 3951.32     185 3957.15   184.1 3994.07  180.31
 3998.51  179.32 4004.33  179.64 4017.74  178.49 4019.04  178.74 4043.17  176.56
 4043.79  176.66 4044.09  176.56 4053.06  175.57 4054.36  175.18 4055.12  175.25
 4077.65  174.16 4077.88  174.11 4082.62   174.1 4084.08  173.88 4086.53  173.85
 4086.99  173.69 4126.52  172.27 4128.21  171.92 4134.72  172.05 4139.54  172.59
 4160.38  171.14 4172.56  174.54 4176.92  177.79  4181.6   180.3 4182.13   180.4
 4182.44  180.36 4186.58   180.3 4190.41  178.98 4194.54  176.28 4202.51  173.11
 4206.26  170.89 4210.55  170.47  4213.7     172 4592.35     170 4681.67     170
 4785.09     170 4815.73     170 4884.67     166 4892.33     162 4902.29     158
 4930.64     152 4961.28     152 4988.09     154  5019.5     152 5030.22     150
 5080.01     160  5136.7     162 5168.11     162 5171.94     168 5191.09     172
 5230.93     172 5234.83  171.49 5257.12  168.57  5258.5  168.82 5267.39  168.63
    5269  168.96 5269.84  168.83 5338.71  169.48 5345.53  167.53 5366.75  168.23
 5368.28   168.8 5405.58  167.63 5405.66  167.61 5440.21  167.25 5440.67  167.67
 5460.89  167.16 5461.96  167.49 5483.03  167.53 5483.34  167.34 5486.56   166.4
 5492.91  167.71 5494.83   167.6 5537.42  168.73 5540.48  168.18 5549.29  168.45
 5549.75  168.33 5592.27  169.15  5594.8  169.77 5598.17  169.72 5605.29  170.33
 5607.67  169.79 5644.59  170.77  5645.2  170.64 5656.92  170.61 5673.55  171.65
 5677.61  170.86 5680.06  171.11 5681.28  170.96 5753.83  171.75 5761.26  172.68
  5765.4  172.52 5766.47  172.75 5844.15  177.56 5847.21  178.29  5856.1  177.47
 5857.47  177.68 5858.09  177.59 5859.46  177.79 5875.71  183.94 5939.06  186.82
 5943.35  186.13 5945.65  186.43 6014.74  186.35 6019.72  187.03 6048.29  187.94
 6049.29  188.28 6067.75  188.17  6070.2  188.58 6077.87  188.52 6079.47  188.84
 6085.22  188.73 6087.13  189.09 6127.43  190.21 6128.12  190.08 6155.85  191.32
  6172.7  194.27 6186.87  195.37 6212.84  196.92 6214.53  196.62 6218.74  197.29
 6292.59  199.51 6327.67   200.5 6337.94  200.48    6340  200.91 6342.15  200.96
 6343.99     201 6346.13  200.65 6348.35  201.15 6354.41  200.87 6388.42  201.62
 6391.48  202.22 6393.71  201.97 6403.89  202.38
BR U #Mann= 5
 3765.71     .15 4892.33     .04 5168.11     .04 5234.83     .15 6342.15     .11
BR D #Sta/Elev= 30
 3795.59  208.27 3845.23  199.38 3974.69  195.35  3987.1  192.33 4000.35  185.56
 4050.68  181.41 4062.09  178.72 4109.28  176.44 4201.98  173.71 4218.06  180.09
 4229.94  173.41 4244.87  171.54 4261.73     173 4681.06     170 4815.73     170
 4884.67     166 4892.33     162 4930.64     152 4988.09     154 5030.22     150
 5080.01     160 5168.11     162 5197.68  160.15    5213  166.36 5228.01  168.68
 5252.07  177.18 5277.88  180.84 5837.48  188.13 6208.63  199.57 6388.57  202.35
BR D #Mann= 4
 3795.59     .15 4681.06     .06 4892.33     .04 5168.11     .06
BC Design=,, 0 ,, 0 ,,,,,,
BC HTab HWMax=205.13
BC Use User HTab Curves=0
BC User HTab FreeFlow(D)= 0

Type RM Length L Ch R = 1 ,17665   ,265,265,265
BEGIN DESCRIPTION:
SALUDA RIVER (I-26 - US)
END DESCRIPTION:
XS GIS Cut Line= 3
      1968995.05       798471.57      1968545.83       796947.19
      1967921.81       795215.91
#Sta/Elev= 30
 3837.82  209.19 3867.32  208.12 3905.62  199.48 3954.65  195.63 4064.65  190.99
 4084.49  185.92 4142.86  180.68  4256.7  175.93 4281.75  179.95    4295  172.97
  4344.1  169.77 4653.43  167.88 4748.27  170.05 4779.75  179.64 4817.21  169.82
 4902.17  167.87 4914.58     164 4918.64 155.988 4921.16     151 4974.79     152
 5055.22     150 5135.66     162 5180.09 162.883 5236.31     164  5242.9     168
  5285.5  175.27 5306.49   180.7 5873.36  187.57 6291.77  199.75 6464.97  202.19
#Mann= 4 ,-1,0
 3837.82     .15       0 4653.43     .15       0 4914.58     .05       0
 5236.31     .15       0
#XS Ineff= 2 , 0
       0    4765  183.14 5328.32       0   181.6
Permanent Ineff=
       F       F
Bank Sta=4918.64,5180.09
XS Rating Curve= 0 ,0
Skew Angle= 40
Exp/Cntr=0.5,0.3

Type RM Length L Ch R = 3 ,17540   ,,,
BEGIN DESCRIPTION:
SALUDA RIVER (I-26 - TOR)
Structure ID: I-26
Detailed Survey Structure
END DESCRIPTION:
Bridge Culvert--1,0,0,-1, 0
Deck Dist Width WeirC Skew NumUp NumDn MinLoCord MaxHiCord MaxSubmerge Is_Ogee
30,160,3,0, 77, 77, 181.7, , 0.95, 0, 2,2,,
3956.5913992.5284033.8174065.9324099.5754135.512 4169.924192.0944211.9744238.736
4266.2634283.8494326.6674328.1974344.2544358.7824382.4854398.5424414.5994430.656
4447.478  4464.34483.4154499.4724517.8234539.2324558.3484578.2284598.1084701.333
 4735.744770.913 4785.02 4801.234815.7734830.5084856.505    48744893.4444913.133
4925.6194941.6764954.7364970.3194975.0674987.8365012.9625027.8035063.6255079.224
5085.0815094.6085119.3985129.1465139.0355153.721 5158.635173.314 5178.255183.189
5192.8545198.5515204.2435208.4855217.6135227.4315237.1645246.8065264.8595273.033
5291.0245306.9665355.0845442.2515513.3615611.9975764.921
     215     214     213     212     211     210     209 208.497  207.87 207.048
 205.965 205.336 203.447     203     202     201     200     199     198     197
     196     195     194     193     192     191     190     189     188     185
     184 183.136 182.811 182.456 182.175 181.861 181.361 181.122 180.859 180.673
  180.55 180.411 180.332 180.247   180.2 180.157 180.115 180.136 180.159 180.246
 180.268 180.331 180.459 180.521 180.598 180.726 180.743 180.791 180.839 180.887
 180.902 180.942 180.983  180.99     181  181.07  181.17  181.25 181.447 181.467
  181.62 181.659     182     183     184     185     186
                                                                                
                                                                                
                                                                                
         179.841 179.516 179.161  178.88 178.566 178.066 177.827 177.564 177.378
 177.255 177.116 177.037 176.952 176.905 176.862  176.82 176.841 176.864 176.951
 176.973 177.036 177.164 177.226 177.303 177.431 177.448 177.496 177.544 177.592
 177.607 177.647 177.688 177.695 177.705 177.775 177.875 177.955 178.152 178.172
 178.325 178.364
3956.5913992.5284033.8174065.9324099.5754135.512 4169.924192.0944211.9744238.736
4266.2634283.8494326.6674328.1974344.2544358.7824382.4854398.5424414.5994430.656
4447.478  4464.34483.4154499.4724517.8234539.2324558.3484578.2284598.1084701.333
 4735.744770.913 4785.02 4801.234815.7734830.5084856.505    48744893.4444913.133
4925.6194941.6764954.7364970.3194975.0674987.8365012.9625027.8035063.6255079.224
5085.0815094.6085119.3985129.1465139.0355153.721 5158.635173.314 5178.255183.189
5192.8545198.5515204.2435208.4855217.6135227.4315237.1645246.8065264.8595273.033
5291.0245306.9665355.0845442.2515513.3615611.9975764.921
     215     214     213     212     211     210     209 208.497  207.87 207.048
 205.965 205.336 203.447     203     202     201     200     199     198     197
     196     195     194     193     192     191     190     189     188     185
     184 183.136 182.811 182.456 182.175 181.861 181.361 181.122 180.859 180.673
  180.55 180.411 180.332 180.247   180.2 180.157 180.115 180.136 180.159 180.246
 180.268 180.331 180.459 180.521 180.598 180.726 180.743 180.791 180.839 180.887
 180.902 180.942 180.983  180.99     181  181.07  181.17  181.25 181.447 181.467
  181.62 181.659     182     183     184     185     186
                                                                                
                                                                                
                                                                                
         179.841 179.516 179.161  178.88 178.566 178.066 177.827 177.564 177.378
 177.255 177.116 177.037 176.952 176.905 176.862  176.82 176.841 176.864 176.951
 176.973 177.036 177.164 177.226 177.303 177.431 177.448 177.496 177.544 177.592
 177.607 177.647 177.688 177.695 177.705 177.775 177.875 177.955 178.152 178.172
 178.325 178.364
Pier Skew, UpSta & Num, DnSta & Num=  ,4824, 2 ,4824, 2 , 0 , 0 , 0 ,0,0
       4       4
   163.5     182
       4       4
   163.5     182
Pier Skew, UpSta & Num, DnSta & Num=  ,4877, 2 ,4877, 2 , 0 , 0 , 0 ,0,0
       4       4
     163     182
       4       4
     163     182
Pier Skew, UpSta & Num, DnSta & Num=  ,4931, 2 ,4931, 2 , 0 , 0 , 0 ,0,0
       4       4
     149  178.57
       4       4
     149  178.57
Pier Skew, UpSta & Num, DnSta & Num=  ,4986, 2 ,4986, 2 , 0 , 0 , 0 ,0,0
       4       4
     150  178.43
       4       4
     150  178.43
Pier Skew, UpSta & Num, DnSta & Num=  ,5038, 2 ,5038, 2 , 0 , 0 , 0 ,0,0
       4       4
     166  177.71
       4       4
     166  177.71
Pier Skew, UpSta & Num, DnSta & Num=  ,5091, 2 ,5091, 2 , 0 , 0 , 0 ,0,0
       4       4
   148.5  178.28
       4       4
   148.5  178.28
Pier Skew, UpSta & Num, DnSta & Num=  ,5145, 2 ,5145, 2 , 0 , 0 , 0 ,0,0
       4       4
     153  178.14
       4       4
     153  178.14
Pier Skew, UpSta & Num, DnSta & Num=  ,5198, 2 ,5198, 2 , 0 , 0 , 0 ,0,0
       4       4
     160     178
       4       4
     160     178
Pier Skew, UpSta & Num, DnSta & Num=  ,5252, 2 ,5252, 2 , 0 , 0 , 0 ,0,0
       4       4
     158  177.85
       4       4
     158  177.85
BR Coef= 1 , 1 , 0 ,1.25, 0 ,,,0.8,0,2,0,
WSPro=,,,, 1 ,,,, 0 ,,,, 0 ,,,,-1 ,-1 ,-1 , 0 , 0 , 0 , 0 , 0
BR U #Sta/Elev= 45
 3837.82  209.19 3867.32  208.12 3905.62  199.48 3954.65  195.63 4018.53  194.05
 4064.65  190.99 4084.49  185.92 4142.86  180.68 4180.94  179.24  4256.7  175.93
 4281.75  179.95    4295  172.97  4344.1  169.77 4400.87  168.89 4430.74  168.06
  4468.2  168.46 4519.53  168.34 4635.35  167.47 4653.43  167.88 4748.27  170.05
  4770.1  177.19 4779.75  179.64 4790.17  177.51 4817.21  169.82 4902.17  167.87
 4914.58     164 4918.64 155.988 4921.16     151 4974.79     152 5028.41   150.5
 5055.22     150 5082.03     155 5121.41     159 5135.66     162 5180.09 162.883
 5236.31     164  5242.9     168  5285.5  175.27 5306.49   180.7 5352.83   181.9
    5720  185.65 5873.36  187.57 6291.77  199.75 6395.42  202.03 6464.97  202.19
BR U #Mann= 3
 3837.82     .05 4918.64     .05 5236.31     .15
BR D #Sta/Elev= 30
    4000  226.35 4103.31  220.79 4184.08   214.7    4254  211.22 4258.98  210.11
 4592.87  193.51 4602.83  192.06 4777.25  186.19 4782.24  185.39 4802.17  170.19
 4812.14     167 4928.24   162.9 4962.96   150.3 5053.24   150.3 5081.02  156.71
 5181.29  164.02  5195.9  163.56 5243.93   167.6 5283.62  178.38 5307.99  183.06
 5332.35  181.92 5437.58  182.35 5507.94  185.31 5512.81  184.75 5522.59  185.88
 5532.46   185.4 5561.67  187.51 5586.09  186.78 5590.98  188.11 5757.07  185.11
BR D #Mann= 3
    4000     .05 4928.24     .05 5181.29     .15
BR D Banks=4928.24,5181.29
BC Design=,, 0 ,, 0 ,,,,,,
BC HTab HWMax=209.19
BC Use User HTab Curves=0
BC User HTab FreeFlow(D)= 0

Type RM Length L Ch R = 1 ,17385   ,20,20,20
XS GIS Cut Line= 3
      1969350.99       798187.76      1968803.81         797056.
       1968156.7       795248.87
#Sta/Elev= 30
  3742.9  210.41  3774.9  210.03  3813.7  214.91  3843.2  214.07  3874.1  209.05
    3909  200.17  3979.5  187.38  4060.3  181.15  4362.4  170.73  4816.4     164
    4825     151    5000     150    5105     162    5175     160  5236.4     164
    5245     168  5399.2  200.73  5410.6  203.27  5616.7   210.4  5778.9  210.87
  5839.7  208.89  6079.7  178.85    6182  176.26  6224.5  172.35  6295.6  178.75
  6337.1  179.49    6530  193.21  6673.3  217.46    6793  225.75  6919.5  234.51
#Mann= 6 ,-1,0
  3742.9     .06       0  3874.1     .15       0  4816.4     .05       0
  5236.4     .15       0  5399.2      .1       0    6793     .11       0
#XS Ineff= 2 , 0
       0 4730.52  180.12  5376.3       0  180.12
Permanent Ineff=
       F       F
Bank Sta=4816.4,5236.4
XS Rating Curve= 0 ,0
Exp/Cntr=0.5,0.3

Type RM Length L Ch R = 1 ,17365   ,296,375,406
BEGIN DESCRIPTION:
SALUDA RIVER (I-26 - DS)
END DESCRIPTION:
XS GIS Cut Line= 3
      1969374.07       798165.33      1968850.37       797056.55
      1968201.88        795246.1
#Sta/Elev= 30
 4117.23  210.41 4141.74  210.03 4171.46  214.91 4194.06  214.07 4217.73  209.05
 4244.47  200.17 4298.47  187.38 4360.37  181.15 4448.24  175.91 4490.67  176.48
 4705.47  167.41 4931.92     165 4939.58     164 4946.16     151 5080.22     150
 5160.66     162 5214.28     160 5261.31     164  5267.9     168 5386.03  200.73
 5394.76  203.27 5552.64   210.4 5723.47  208.89 5907.32  178.85 5985.69  176.26
 6018.24  172.35 6252.27  193.21 6362.04  217.46 6453.74  225.75 6550.65  234.51
#Mann= 6 ,-1,0
 4117.23     .06       0 4217.73     .15       0 4939.58     .05       0
 5261.31     .15       0 5386.03      .1       0 6453.74     .11       0
#XS Ineff= 2 , 0
    1250 4730.52  180.12  5376.3    1250  180.12
Permanent Ineff=
       F       F
Bank Sta=4931.92,5261.31
XS Rating Curve= 0 ,0
Skew Angle= 40
Exp/Cntr=0.5,0.3

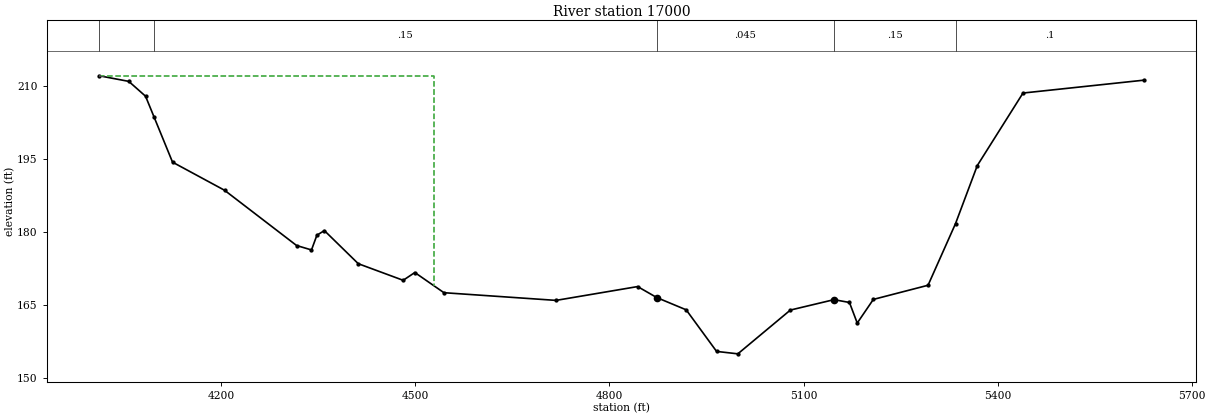
Type RM Length L Ch R = 1 ,17000   ,500,400,251
BEGIN DESCRIPTION:
SALUDA RIVER 37.0
END DESCRIPTION:
XS GIS Cut Line= 3
       1969399.2       798164.06      1969175.35       797137.59
      1969019.47       796487.82
#Sta/Elev= 30
 4011.22  212.12 4056.89  210.97 4082.83  207.92  4095.7  203.74 4124.55  194.36
 4204.99  188.58 4316.34  177.22 4339.36  176.31 4347.73  179.34 4359.28  180.29
 4411.72  173.48 4481.07  170.07 4499.11  171.67 4544.12  167.52  4717.4  165.94
 4843.51  168.78  4873.3  166.51 4918.59     164 4965.57  155.45 4998.46  154.95
 5079.65  163.95 5147.12  166.09 5170.99  165.51 5183.02  161.28 5207.92  166.14
 5292.49  169.05 5334.97  181.73 5368.61  193.66 5439.27  208.57 5626.37  211.22
#Mann= 5 ,-1,0
 4011.22     .06       0  4095.7     .15       0  4873.3    .045       0
 5147.12     .15       0 5334.97      .1       0
#XS Ineff= 2 , 0
     300 4528.62     212             300
Permanent Ineff=
       F       F
Bank Sta=4873.3,5147.12
XS Rating Curve= 0 ,0
Skew Angle= 20
Exp/Cntr=0.3,0.1

--- CCR_SALUDA_RIVER.g13 (geometry) ---

Geom Title=REV
Program Version=6.10

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
River Reach=SALUDA RIVER    ,Reach-1

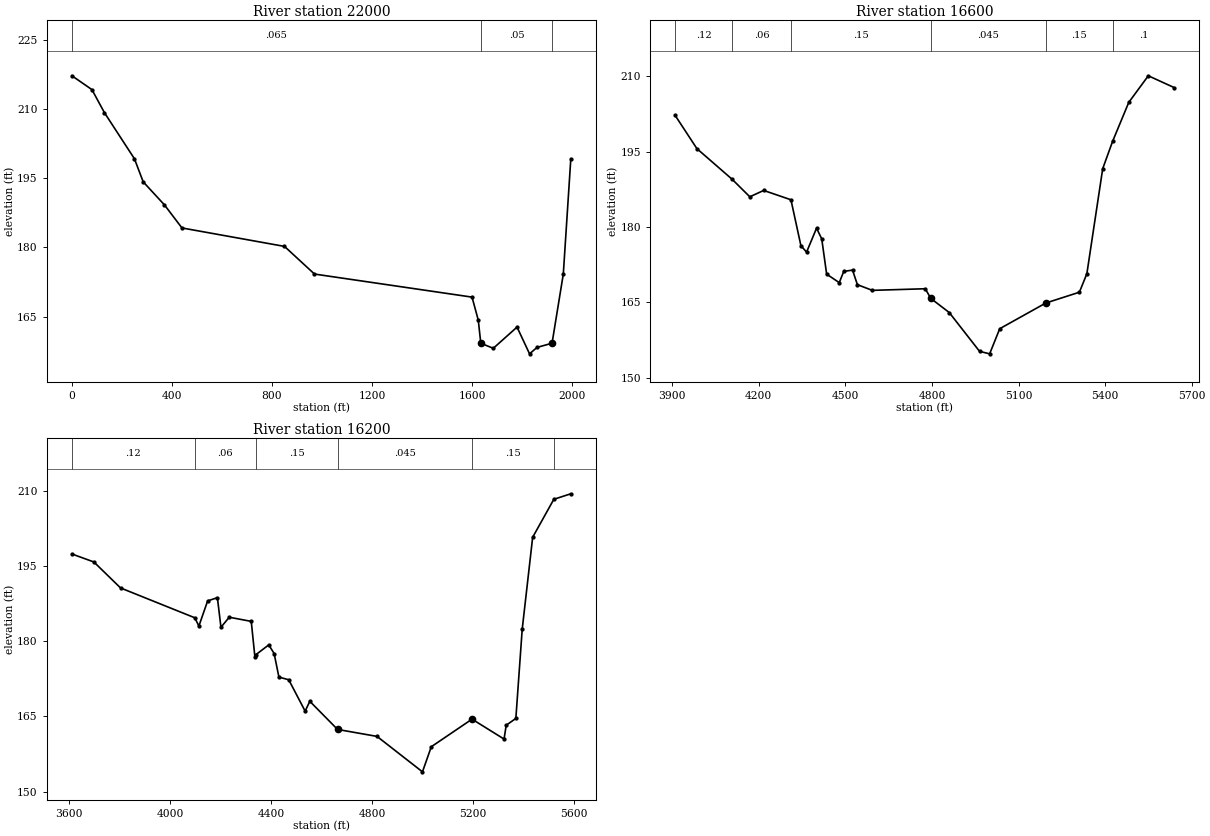
Type RM Length L Ch R = 1 ,22000   ,3200,3200,3200
BEGIN DESCRIPTION:
FEMA XS: I
END DESCRIPTION:
XS GIS Cut Line= 2
     1964713.343      798155.587     1964453.567      796811.327
#Sta/Elev= 19
       0  217.22      80  214.22     130  209.22     250  199.22     285  194.22
     370  189.22     440  184.22     850  180.22     970  174.22    1600  169.22
    1625  164.22    1635  159.22    1685  158.12    1780  162.72    1830  156.92
    1860  158.32    1920  159.22    1965  174.22    1995  199.22
#Mann= 3 ,0,0
       0    .065       0    1635     .05       0    1920    .065       0
Bank Sta=1635,1920
XS Rating Curve= 0 ,0
Exp/Cntr=0.3,0.1

Type RM Length L Ch R = 1 ,16600   ,671,400,215
BEGIN DESCRIPTION:
SALUDA RIVER 36.0
END DESCRIPTION:
XS GIS Cut Line= 3
       1970093.6       797930.83      1969538.96       796992.96
      1969111.71       796517.66
#Sta/Elev= 30
  3910.4   202.2  3985.7   195.6  4107.9   189.5    4169  186.02    4217  187.29
  4311.5  185.43  4346.1  176.28  4365.7  175.02  4400.2  179.78  4418.2  177.65
  4435.2  170.63  4478.9  168.95  4494.5  171.18    4525  171.44  4541.7  168.54
  4593.5  167.41  4776.9  167.73  4796.2   165.8    4860     163    4965  155.28
    5000  154.78    5035  159.78  5194.6  164.89    5311  167.04  5336.9  170.72
  5391.8  191.62  5426.1  197.06  5482.1  204.81  5549.8   210.1  5639.1  207.76
#Mann= 6 ,-1,0
  3910.4     .12       0  4107.9     .06       0  4311.5     .15       0
  4796.2    .045       0  5194.6     .15       0  5426.1      .1       0
Bank Sta=4796.2,5194.6
XS Rating Curve= 0 ,0
Exp/Cntr=0.3,0.1

Type RM Length L Ch R = 1 ,16200   ,568,500,361
BEGIN DESCRIPTION:
SALUDA RIVER 35.0
END DESCRIPTION:
XS GIS Cut Line= 3
      1971090.43       797146.26      1969782.51       796678.06
      1969215.04       796524.44
#Sta/Elev= 30
  3610.8  197.35  3697.8  195.76  3803.7  190.58  4097.7  184.64    4114  182.99
  4148.6     188  4187.3  188.65  4201.4  182.75  4234.3  184.75  4321.5  183.92
  4335.8  176.91  4339.7  177.28  4390.9  179.24  4412.2  177.51  4431.1  172.82
    4470  172.29  4535.1  166.03  4553.5     168  4663.5  162.39    4820     161
    5000  153.94    5035  158.94  5196.4  164.44  5323.4  160.47  5331.9  163.23
  5370.1  164.58  5395.3  182.36  5436.7  200.68  5520.6  208.25  5587.9  209.35
#Mann= 6 ,-1,0
  3610.8     .12       0  4097.7     .06       0  4339.7     .15       0
  4663.5    .045       0  5196.4     .15       0  5520.6      .1       0
Bank Sta=4663.5,5196.4
XS Rating Curve= 0 ,0
Exp/Cntr=0.3,0.1

--- CCR_SALUDA_RIVER.g27 (geometry) ---

Geom Title=NAT
Program Version=6.10

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
River Reach=SALUDA RIVER    ,Reach-1