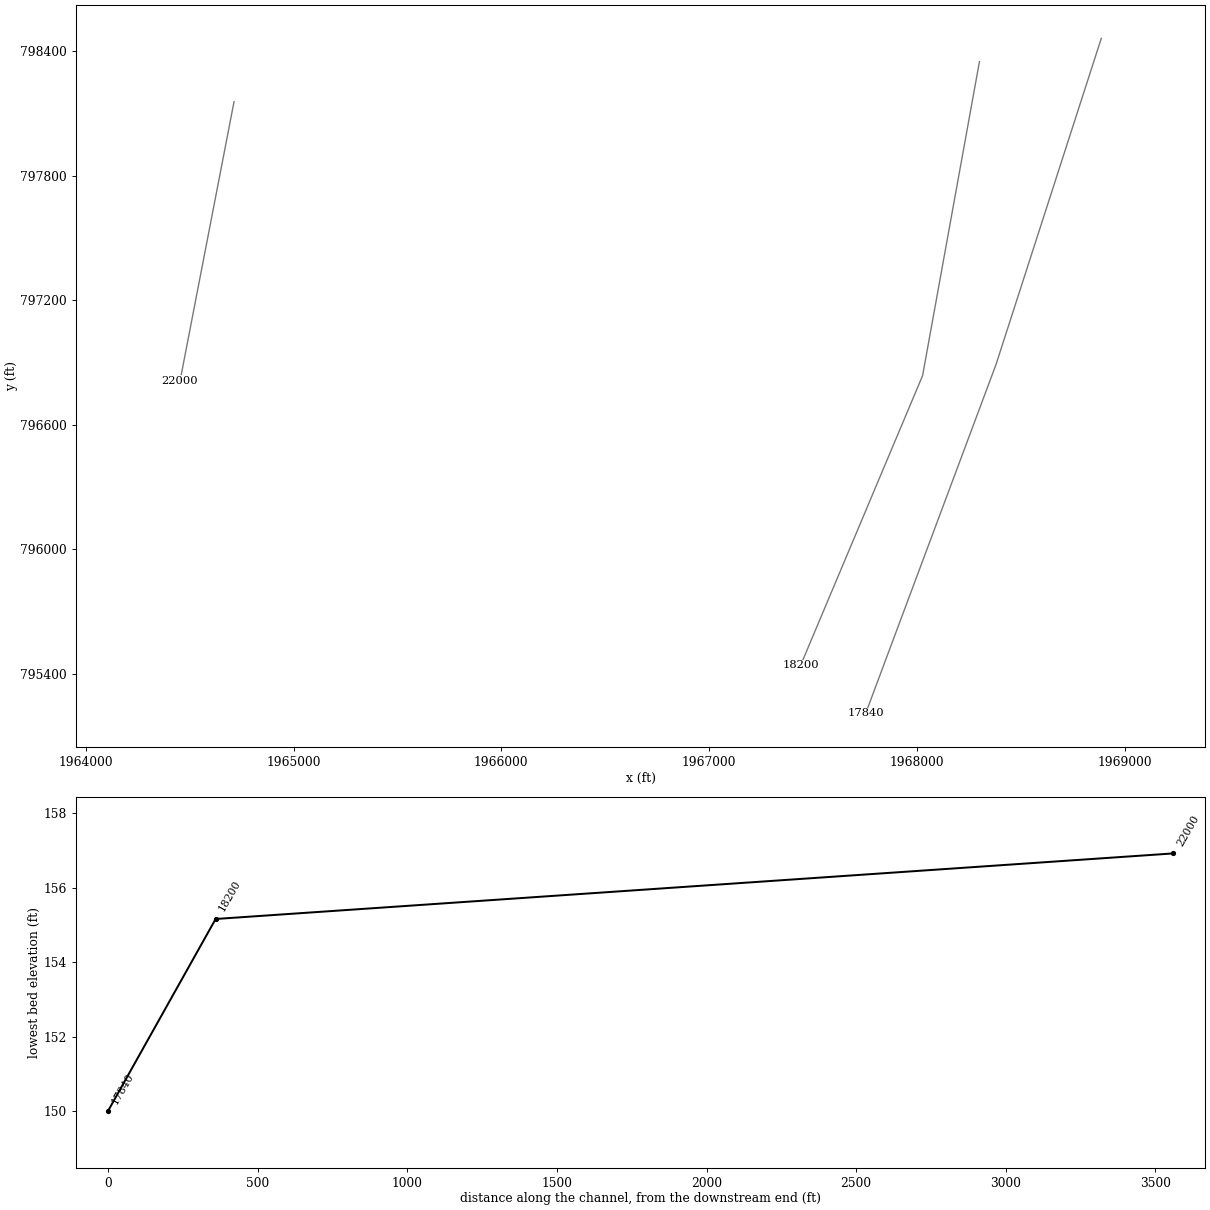
HEC-RAS study CCR_SALUDA_RIVER.prj: CCR SALUDA RIVER Detailed Study

--- CCR_SALUDA_RIVER.g27 (geometry) --- (continued)

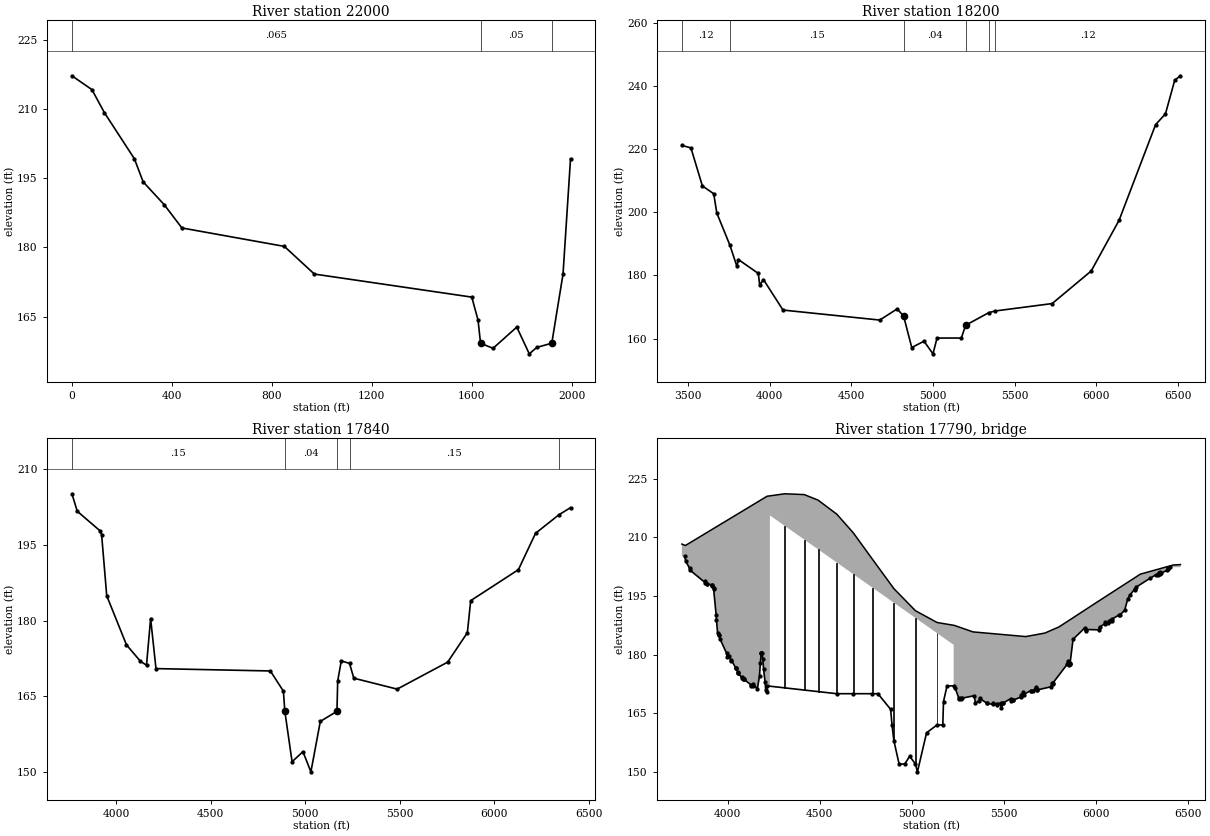
Type RM Length L Ch R = 1 ,22000   ,3200,3200,3200
BEGIN DESCRIPTION:
FEMA XS: I
END DESCRIPTION:
XS GIS Cut Line= 2
     1964713.343      798155.587     1964453.567      796811.327
#Sta/Elev= 19
       0  217.22      80  214.22     130  209.22     250  199.22     285  194.22
     370  189.22     440  184.22     850  180.22     970  174.22    1600  169.22
    1625  164.22    1635  159.22    1685  158.12    1780  162.72    1830  156.92
    1860  158.32    1920  159.22    1965  174.22    1995  199.22
#Mann= 3 ,0,0
       0    .065       0    1635     .05       0    1920    .065       0
Bank Sta=1635,1920
XS Rating Curve= 0 ,0
Exp/Cntr=0.3,0.1

Type RM Length L Ch R = 1 ,18200   ,399,360,425
BEGIN DESCRIPTION:
SALUDA RIVER 44.0
END DESCRIPTION:
XS GIS Cut Line= 3
      1968300.98       798348.76      1968027.38       796836.81
      1967440.11       795441.03
#Sta/Elev= 30
  3463.5   221.2  3518.9  220.41    3589  208.36  3658.5  205.88  3677.1   199.8
    3757  189.63  3800.2  182.87  3809.3  185.04  3931.2  180.63  3939.6  176.98
  3962.8  178.68  4082.2  169.03  4674.2  165.86  4780.6  169.39    4820  167.16
    4870  157.16    4945  159.16    5000  155.16  5024.7  160.16  5173.5  160.17
  5199.8  164.22  5340.1  168.17  5377.5  168.72  5729.2  171.09  5968.2  181.42
  6138.8   197.5  6361.9  227.77  6422.4   231.2    6479  241.85  6514.3  243.26
#Mann= 6 ,-1,0
  3463.5     .12       0    3757     .15       0    4820     .04       0
  5199.8     .15       0  5340.1     .04       0  5377.5     .12       0
#XS Ineff= 2 , 0
Permanent Ineff=
       F       F
Bank Sta=4820,5199.8
XS Rating Curve= 0 ,0
Exp/Cntr=0.3,0.1

Type RM Length L Ch R = 1 ,17840   ,77,90,170
BEGIN DESCRIPTION:
SALUDA RIVER (I-26 Ramp - US)
END DESCRIPTION:
XS GIS Cut Line= 3
       1968887.4       798461.11      1968380.66       796890.12
      1967753.47       795210.18
#Sta/Elev= 30
 3765.71  205.13 3793.98  201.67 3916.01  197.74 3922.91  197.01 3949.95  184.91
 4054.36  175.18 4128.21  171.92 4160.38  171.14 4182.13   180.4 4210.55  170.47
 4815.73     170 4884.67     166 4892.33     162 4930.64     152 4988.09     154
 5030.22     150 5080.01     160 5168.11     162 5171.94     168 5191.09     172
 5234.83  171.49 5257.12  168.57 5486.56   166.4 5753.83  171.75 5858.09  177.59
 5875.71  183.94 6128.12  190.08 6218.74  197.29 6342.15  200.96 6403.89  202.38
#Mann= 5 ,-1,0
 3765.71     .15       0 4892.33     .04       0 5168.11     .04       0
 5234.83     .15       0 6342.15     .11       0
#XS Ineff= 2 , 0
Permanent Ineff=
       F       F
Bank Sta=4892.33,5168.11
XS Rating Curve= 0 ,0
Skew Angle= 40
Exp/Cntr=0.3,0.1

Type RM Length L Ch R = 3 ,17790   ,,,
BEGIN DESCRIPTION:
SALUDA RIVER (I-26 Ramp - TOR)
Structure ID: I-26 Ramp
Detailed Survey Structure
END DESCRIPTION:
Bridge Culvert--1,0,-1,-1, 0
Deck Dist Width WeirC Skew NumUp NumDn MinLoCord MaxHiCord MaxSubmerge Is_Ogee
32.5,35,3,40, 25, 25, , , 0.95, 0, 1,1,,
3750.8513770.0024213.6964229.0164229.0164309.6814415.625 4490.854592.3514681.672
4785.0884902.2935019.4985136.7025227.0965227.0965230.9265331.9675618.3915722.573
5799.4086011.5256241.0326419.5976459.125
   208.3  207.93  220.54  220.64  220.64  221.17  220.96  219.54  215.95  211.19
  204.47   196.9  191.24  188.23  187.51  187.51  187.48  185.82  184.62  185.52
   187.1  193.61   200.6  202.94  203.05
                                  215.64  212.96  209.45  206.95  203.58  200.61
  197.18  193.29   189.4  185.51  182.51
                                        
3750.8513770.0024213.6964229.0164229.0164309.6814415.625 4490.854592.3514681.672
4785.0884902.2935019.4985136.7025227.0965227.0965230.9265331.9675618.3915722.573
5799.4086011.5256241.0326419.5976459.125
   208.3  207.93  220.54  220.64  220.64  221.17  220.96  219.54  215.95  211.19
  204.47   196.9  191.24  188.23  187.51  187.51  187.48  185.82  184.62  185.52
   187.1  193.61   200.6  202.94  203.05
                                  215.64  212.96  209.45  206.95  203.58  200.61
  197.18  193.29   189.4  185.51  182.51
                                        
Pier Skew, UpSta & Num, DnSta & Num=  ,4309.681, 2 ,4309.681, 2 , 0 , 0 , 0 ,0,0
       5       5
   194.5  212.96
       5       5
   194.5  212.96
Pier Skew, UpSta & Num, DnSta & Num=  ,4415.625, 2 ,4415.625, 2 , 0 , 0 , 0 ,0,0
       5       5
  192.72  209.45
       5       5
  192.72  209.45
Pier Skew, UpSta & Num, DnSta & Num=  ,4490.85, 2 ,4490.85, 2 , 0 , 0 , 0 ,0,0
       5       5
     177  206.95
       5       5
     177  206.95
Pier Skew, UpSta & Num, DnSta & Num=  ,4592.351, 2 ,4592.351, 2 , 0 , 0 , 0 ,0,0
       5       5
     168  203.58
       5       5
     168  203.58
Pier Skew, UpSta & Num, DnSta & Num=  ,4681.672, 2 ,4681.672, 2 , 0 , 0 , 0 ,0,0
       5       5
     168  200.62
       5       5
     168  200.62
Pier Skew, UpSta & Num, DnSta & Num=  ,4785.088, 2 ,4785.088, 2 , 0 , 0 , 0 ,0,0
       5       5
     168  197.18
       5       5
     168  197.18
Pier Skew, UpSta & Num, DnSta & Num=  ,4902.293, 2 ,4902.293, 2 , 0 , 0 , 0 ,0,0
       5       5
     156  193.29
       5       5
     156  193.29
Pier Skew, UpSta & Num, DnSta & Num=  ,5019.498, 2 ,5019.498, 2 , 0 , 0 , 0 ,0,0
       5       5
     150   189.4
       5       5
     150   189.4
Pier Skew, UpSta & Num, DnSta & Num=  ,5136.702, 2 ,5136.702, 2 , 0 , 0 , 0 ,0,0
       5       5
     160  185.51
       5       5
     160  185.51
BR Coef= 1 , 1 , 0 ,1.25, 0 ,,,0.8,0,2,0,
WSPro=,,,, 1 ,,,, 0 ,,,, 0 ,,,,-1 ,-1 ,-1 , 0 , 0 , 0 , 0 , 0
BR U #Sta/Elev= 153
 3765.71  205.13 3772.15  203.89 3792.52  202.11 3793.98  201.67 3876.33  198.46
  3878.7  198.94 3885.83  198.07 3886.36  198.17 3912.64  197.83 3914.09  197.46
 3916.01  197.74 3922.91  197.01 3923.14  196.83 3937.23  190.05 3938.53  188.92
 3944.66  185.64 3949.95  184.91 3951.32     185 3957.15   184.1 3994.07  180.31
 3998.51  179.32 4004.33  179.64 4017.74  178.49 4019.04  178.74 4043.17  176.56
 4043.79  176.66 4044.09  176.56 4053.06  175.57 4054.36  175.18 4055.12  175.25
 4077.65  174.16 4077.88  174.11 4082.62   174.1 4084.08  173.88 4086.53  173.85
 4086.99  173.69 4126.52  172.27 4128.21  171.92 4134.72  172.05 4139.54  172.59
 4160.38  171.14 4172.56  174.54 4176.92  177.79  4181.6   180.3 4182.13   180.4
 4182.44  180.36 4186.58   180.3 4190.41  178.98 4194.54  176.28 4202.51  173.11
 4206.26  170.89 4210.55  170.47  4213.7     172 4592.35     170 4681.67     170
 4785.09     170 4815.73     170 4884.67     166 4892.33     162 4902.29     158
 4930.64     152 4961.28     152 4988.09     154  5019.5     152 5030.22     150
 5080.01     160  5136.7     162 5168.11     162 5171.94     168 5191.09     172
 5230.93     172 5234.83  171.49 5257.12  168.57  5258.5  168.82 5267.39  168.63
    5269  168.96 5269.84  168.83 5338.71  169.48 5345.53  167.53 5366.75  168.23
 5368.28   168.8 5405.58  167.63 5405.66  167.61 5440.21  167.25 5440.67  167.67
 5460.89  167.16 5461.96  167.49 5483.03  167.53 5483.34  167.34 5486.56   166.4
 5492.91  167.71 5494.83   167.6 5537.42  168.73 5540.48  168.18 5549.29  168.45
 5549.75  168.33 5592.27  169.15  5594.8  169.77 5598.17  169.72 5605.29  170.33
 5607.67  169.79 5644.59  170.77  5645.2  170.64 5656.92  170.61 5673.55  171.65
 5677.61  170.86 5680.06  171.11 5681.28  170.96 5753.83  171.75 5761.26  172.68
  5765.4  172.52 5766.47  172.75 5844.15  177.56 5847.21  178.29  5856.1  177.47
 5857.47  177.68 5858.09  177.59 5859.46  177.79 5875.71  183.94 5939.06  186.82
 5943.35  186.13 5945.65  186.43 6014.74  186.35 6019.72  187.03 6048.29  187.94
 6049.29  188.28 6067.75  188.17  6070.2  188.58 6077.87  188.52 6079.47  188.84
 6085.22  188.73 6087.13  189.09 6127.43  190.21 6128.12  190.08 6155.85  191.32
  6172.7  194.27 6186.87  195.37 6212.84  196.92 6214.53  196.62 6218.74  197.29
 6292.59  199.51 6327.67   200.5 6337.94  200.48    6340  200.91 6342.15  200.96
 6343.99     201 6346.13  200.65 6348.35  201.15 6354.41  200.87 6388.42  201.62
 6391.48  202.22 6393.71  201.97 6403.89  202.38
BR U #Mann= 5
 3765.71     .15 4892.33     .04 5168.11     .04 5234.83     .15 6342.15     .11
BR D #Sta/Elev= 30
 3795.59  208.27 3845.23  199.38 3974.69  195.35  3987.1  192.33 4000.35  185.56
 4050.68  181.41 4062.09  178.72 4109.28  176.44 4201.98  173.71 4218.06  180.09
 4229.94  173.41 4244.87  171.54 4261.73     173 4681.06     170 4815.73     170
 4884.67     166 4892.33     162 4930.64     152 4988.09     154 5030.22     150
 5080.01     160 5168.11     162 5197.68  160.15    5213  166.36 5228.01  168.68
 5252.07  177.18 5277.88  180.84 5837.48  188.13 6208.63  199.57 6388.57  202.35
BR D #Mann= 4
 3795.59     .15 4681.06     .06 4892.33     .04 5168.11     .06
BC Design=,, 0 ,, 0 ,,,,,,
BC HTab HWMax=205.13
BC Use User HTab Curves=0
BC User HTab FreeFlow(D)= 0