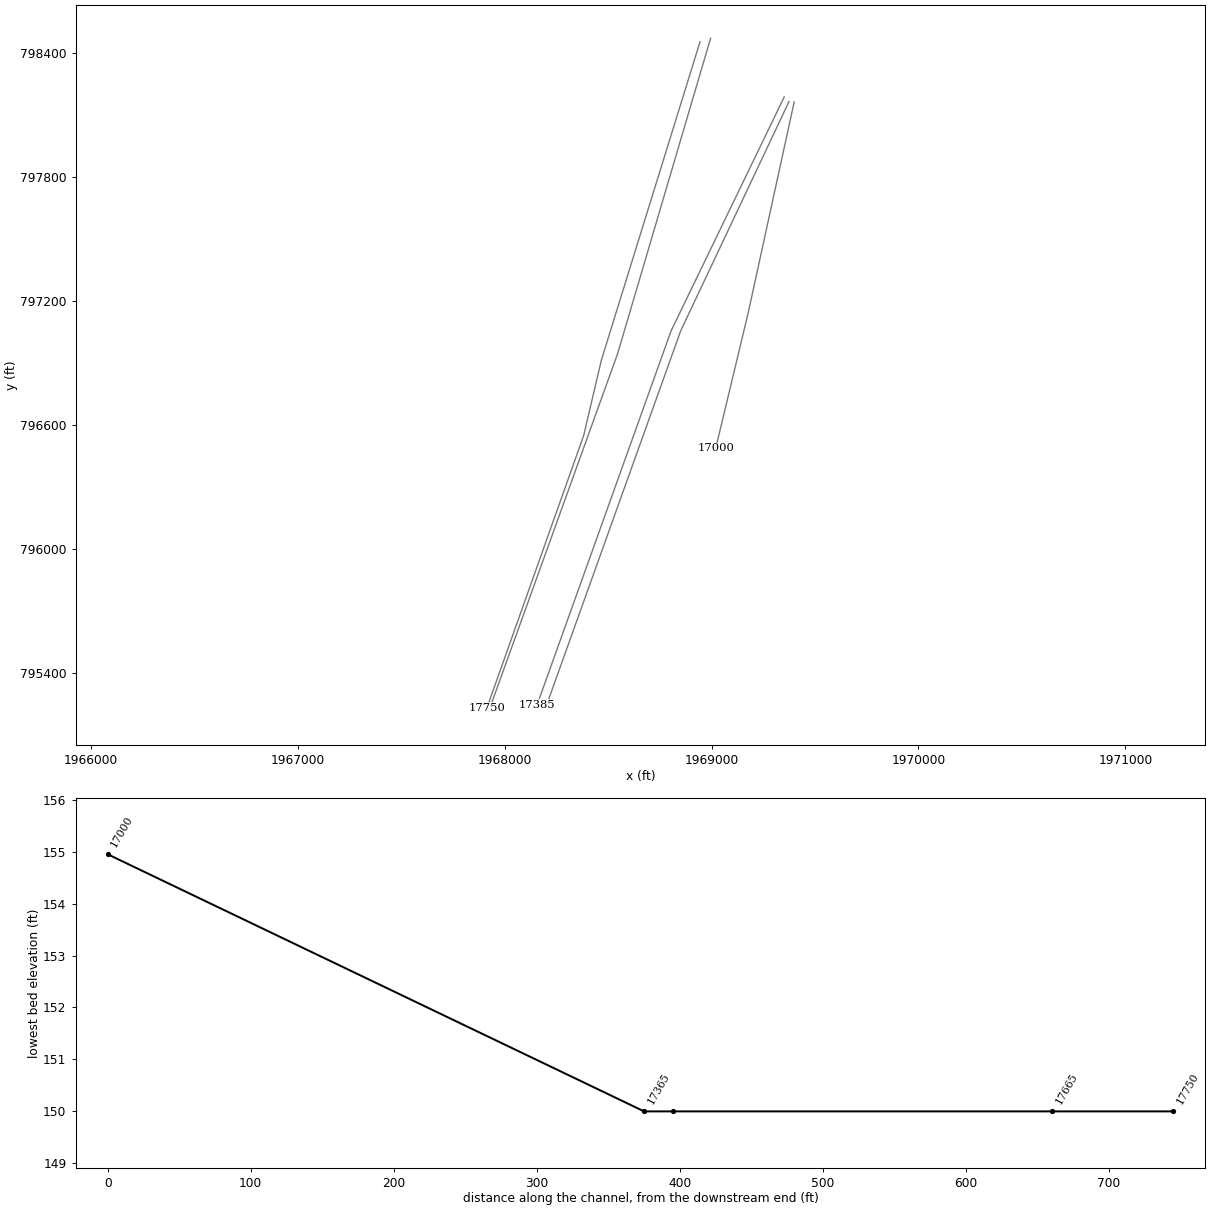
HEC-RAS study CCR_SALUDA_RIVER.prj: CCR SALUDA RIVER Detailed Study

--- CCR_SALUDA_RIVER.g27 (geometry) --- (continued)

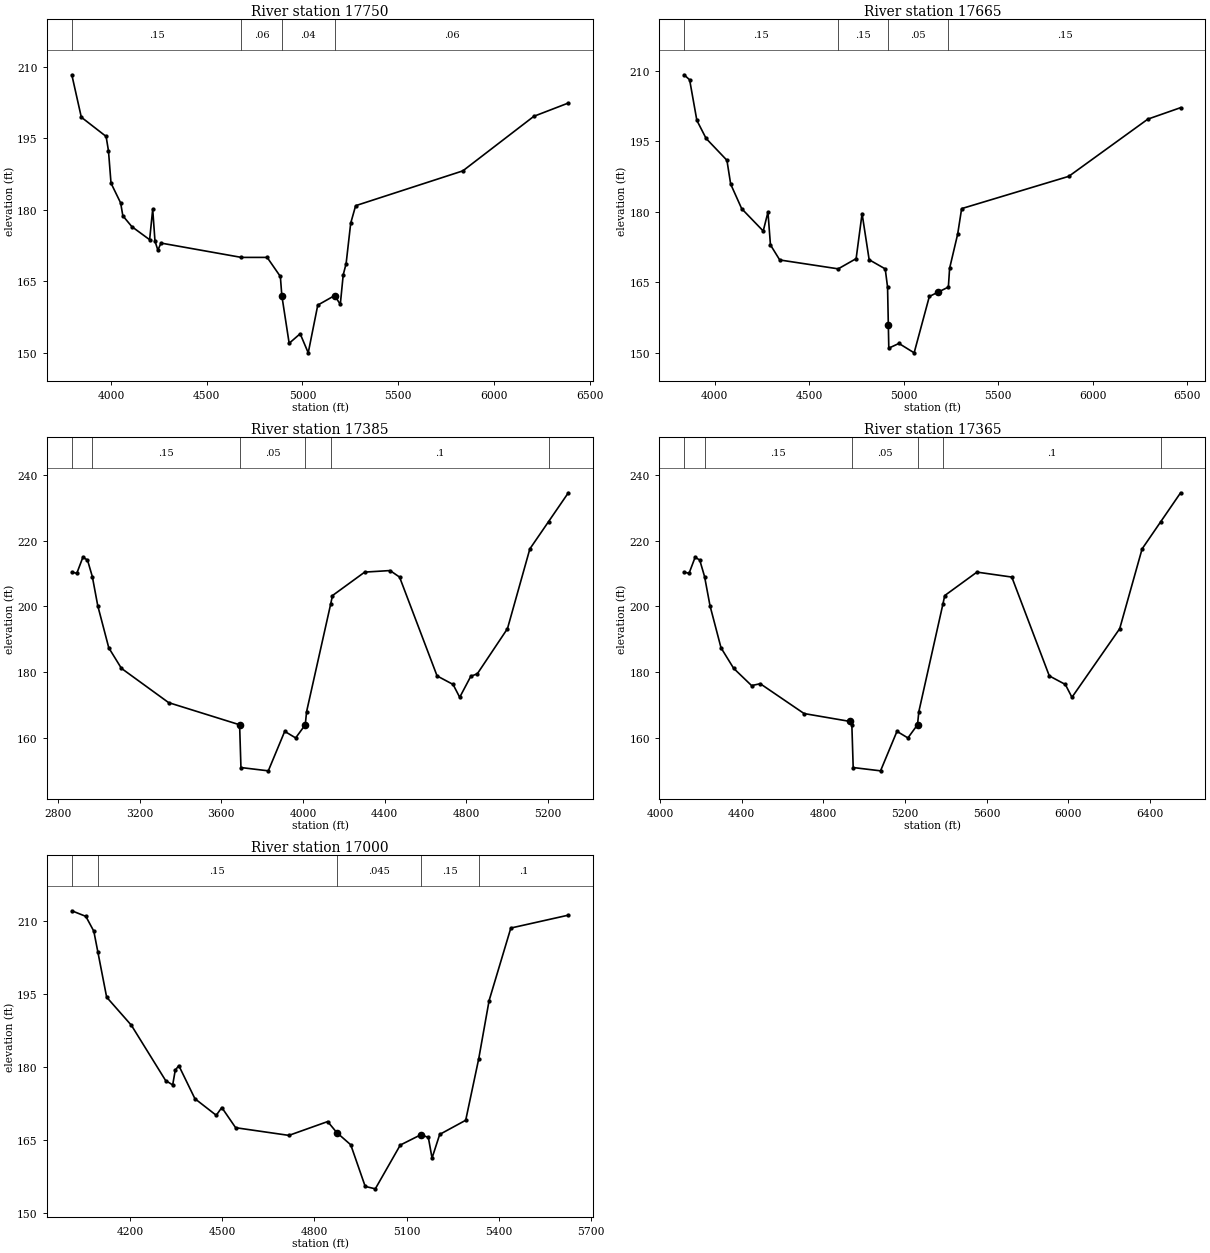
Type RM Length L Ch R = 1 ,17750   ,67,85,34
BEGIN DESCRIPTION:
SALUDA RIVER (I-26 Ramp - DS)
END DESCRIPTION:
XS GIS Cut Line= 4
      1968944.07       798454.82      1968467.06       796915.33
      1968381.51       796550.92      1967913.41       795232.68
#Sta/Elev= 30
 3795.59  208.27 3845.23  199.38 3974.69  195.35  3987.1  192.33 4000.35  185.56
 4050.68  181.41 4062.09  178.72 4109.28  176.44 4201.98  173.71 4218.06  180.09
 4229.94  173.41 4244.87  171.54 4261.73     173 4681.06     170 4815.73     170
 4884.67     166 4892.33     162 4930.64     152 4988.09     154 5030.22     150
 5080.01     160 5168.11     162 5197.68  160.15    5213  166.36 5228.01  168.68
 5252.07  177.18 5277.88  180.84 5837.48  188.13 6208.63  199.57 6388.57  202.35
#Mann= 4 ,-1,0
 3795.59     .15       0 4681.06     .06       0 4892.33     .04       0
 5168.11     .06       0
#XS Ineff= 2 , 0
Permanent Ineff=
       F       F
Bank Sta=4892.33,5168.11
XS Rating Curve= 0 ,0
Skew Angle= 40
Exp/Cntr=0.3,0.1

Type RM Length L Ch R = 1 ,17665   ,265,265,265
BEGIN DESCRIPTION:
SALUDA RIVER (I-26 - US)
END DESCRIPTION:
XS GIS Cut Line= 3
      1968995.05       798471.57      1968545.83       796947.19
      1967921.81       795215.91
#Sta/Elev= 30
 3837.82  209.19 3867.32  208.12 3905.62  199.48 3954.65  195.63 4064.65  190.99
 4084.49  185.92 4142.86  180.68  4256.7  175.93 4281.75  179.95    4295  172.97
  4344.1  169.77 4653.43  167.88 4748.27  170.05 4779.75  179.64 4817.21  169.82
 4902.17  167.87 4914.58     164 4918.64 155.988 4921.16     151 4974.79     152
 5055.22     150 5135.66     162 5180.09 162.883 5236.31     164  5242.9     168
  5285.5  175.27 5306.49   180.7 5873.36  187.57 6291.77  199.75 6464.97  202.19
#Mann= 4 ,-1,0
 3837.82     .15       0 4653.43     .15       0 4914.58     .05       0
 5236.31     .15       0
#XS Ineff= 2 , 0
Permanent Ineff=
       F       F
Bank Sta=4918.64,5180.09
XS Rating Curve= 0 ,0
Skew Angle= 40
Exp/Cntr=0.3,0.1

Type RM Length L Ch R = 1 ,17385   ,20,20,20
XS GIS Cut Line= 3
      1969350.99       798187.76      1968803.81         797056.
       1968156.7       795248.87
#Sta/Elev= 30
2867.228  210.412891.741  210.032921.464  214.912944.062  214.072967.733  209.05
2994.468  200.173048.474  187.38 3110.37  181.153341.792  170.733689.576     164
3696.164     1513830.222     1503910.657     162 3964.28     1604011.315     164
4017.903     1684136.027  200.73 4144.76  203.274302.642   210.44426.894  210.87
 4473.47  208.89 4657.32  178.854735.687  176.264768.244  172.354822.709  178.75
  4854.5  179.49 5002.27  193.215112.044  217.46 5203.74  225.755300.645  234.51
#Mann= 6 ,-1,0
2867.228     .06       02967.733     .15       03689.576     .05       0
4011.315     .15       04136.027      .1       0 5203.74     .11       0
#XS Ineff= 2 , 0
Permanent Ineff=
       F       F
Bank Sta=3689.576,4011.315
XS Rating Curve= 0 ,0
Skew Angle= 40
Exp/Cntr=0.3,0.1

Type RM Length L Ch R = 1 ,17365   ,296,375,406
BEGIN DESCRIPTION:
SALUDA RIVER (I-26 - DS)
END DESCRIPTION:
XS GIS Cut Line= 3
      1969374.07       798165.33      1968850.37       797056.55
      1968201.88        795246.1
#Sta/Elev= 30
 4117.23  210.41 4141.74  210.03 4171.46  214.91 4194.06  214.07 4217.73  209.05
 4244.47  200.17 4298.47  187.38 4360.37  181.15 4448.24  175.91 4490.67  176.48
 4705.47  167.41 4931.92     165 4939.58     164 4946.16     151 5080.22     150
 5160.66     162 5214.28     160 5261.31     164  5267.9     168 5386.03  200.73
 5394.76  203.27 5552.64   210.4 5723.47  208.89 5907.32  178.85 5985.69  176.26
 6018.24  172.35 6252.27  193.21 6362.04  217.46 6453.74  225.75 6550.65  234.51
#Mann= 6 ,-1,0
 4117.23     .06       0 4217.73     .15       0 4939.58     .05       0
 5261.31     .15       0 5386.03      .1       0 6453.74     .11       0
#XS Ineff= 2 , 0
Permanent Ineff=
       F       F
Bank Sta=4931.92,5261.31
XS Rating Curve= 0 ,0
Skew Angle= 40
Exp/Cntr=0.3,0.1

Type RM Length L Ch R = 1 ,17000   ,500,400,251
BEGIN DESCRIPTION:
SALUDA RIVER 37.0
END DESCRIPTION:
XS GIS Cut Line= 3
       1969399.2       798164.06      1969175.35       797137.59
      1969019.47       796487.82
#Sta/Elev= 30
 4011.22  212.12 4056.89  210.97 4082.83  207.92  4095.7  203.74 4124.55  194.36
 4204.99  188.58 4316.34  177.22 4339.36  176.31 4347.73  179.34 4359.28  180.29
 4411.72  173.48 4481.07  170.07 4499.11  171.67 4544.12  167.52  4717.4  165.94
 4843.51  168.78  4873.3  166.51 4918.59     164 4965.57  155.45 4998.46  154.95
 5079.65  163.95 5147.12  166.09 5170.99  165.51 5183.02  161.28 5207.92  166.14
 5292.49  169.05 5334.97  181.73 5368.61  193.66 5439.27  208.57 5626.37  211.22
#Mann= 5 ,-1,0
 4011.22     .06       0  4095.7     .15       0  4873.3    .045       0
 5147.12     .15       0 5334.97      .1       0
#XS Ineff= 2 , 0
Permanent Ineff=
       F       F
Bank Sta=4873.3,5147.12
XS Rating Curve= 0 ,0
Skew Angle= 20
Exp/Cntr=0.3,0.1